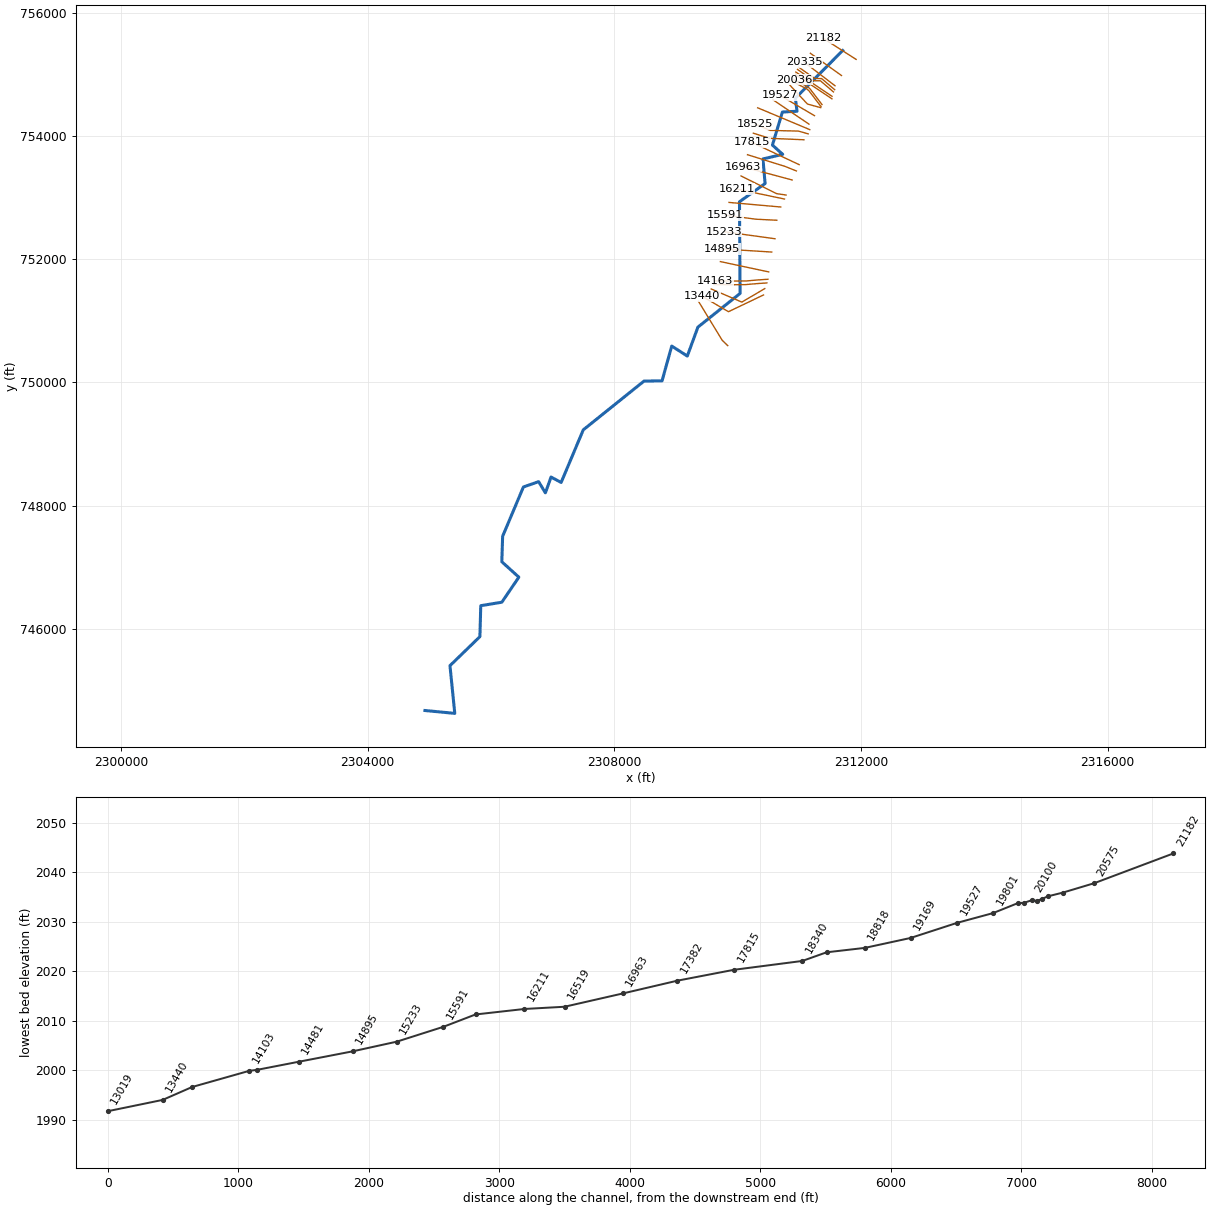
--- CHERRYFK.prj (project) ---

Proj Title=CHERRYFK
Current Plan=p01
Default Exp/Contr=0,0
English Units
Geom File=g01
Flow File=f01
Plan File=p01
BEGIN DESCRIPTION:
----------MODEL BY WOOD PLC 2022----------
AFH study
Randolph County, WV
HEC-RAS Version: RAS 6.2
Vertical Datum: NAVD88
Projection: NAD 1983 StatePlane West Virginia S FIPS 4702 (US Feet)
Terrain: 1-meter LIDAR (FEMA Region III 3DEP collected 2016-2018)
Land Use: 2019 NLCD
Hydrologic Method:
WV SIR2010-5033 regression equations
Additional Model Notes:
END DESCRIPTION:
DSS Export Rating Curves= 0
DSS Export Rating Curve Sorted= 0
DSS Export Volume Flow Curves= 0
DXF OffsetX= 0
DXF OffsetY= 0
DXF ScaleX= 0
DXF ScaleY= 0

--- CHERRYFK.p01 (plan) ---

Plan Title=Floodplain
Program Version=6.10
Short Identifier=Floodplain
Geom File=g01
Flow File=f01
Subcritical Flow
K Sum by GR= 0
Std Step Tol= 0.01
Critical Tol= 0.01
Num of Std Step Trials= 20
Max Error Tol= 0.3
Flow Tol Ratio= 0.001
Split Flow NTrial= 30
Split Flow Tol= 0.02
Split Flow Ratio= 0.02
Log Output Level= 0
Friction Slope Method= 1
Unsteady Friction Slope Method= 2
Unsteady Bridges Friction Slope Method= 1
Parabolic Critical Depth
Global Vel Dist= 0 , 0 , 0
Global Log Level= 0
CheckData=True
Encroach Param=-1 ,0,0, 0
Mapping Interval=1HOUR
Computation Time Step Use Courant=        0
Computation Time Step Use Time Series=    0
Computation Time Step Count To Double=0
Computation Time Step Max Doubling=0
Computation Time Step Max Halving=0
Computation Time Step Residence Courant=0
Run HTab= 0
Run UNet= 0
Run Sediment= 0
Run PostProcess= 0
Run WQNet= 0
Run RASMapper=-1
UNET Theta= 0
UNET Theta Warmup= 0
UNET ZTol= 0
UNET ZSATol= 0
UNET MxIter= 0
UNET Max Iter WO Improvement= 0
UNET MaxInSteps= 0
UNET DtIC= 0
UNET DtMin= 0
UNET MaxCRTS= 0
UNET WFStab= 0
UNET SFStab= 0
UNET WFX= 1
UNET SFX= 1
UNET Gravity=32.174
UNET 1D Methodology=Finite Difference
UNET DSS MLevel= 1
UNET Pardiso=0
UNET DZMax Abort= 0
UNET Use Existing IB Tables= 0
UNET Froude Reduction=False
UNET Froude Limit= 0
UNET Froude Power= 0
UNET D1 Cores= 0
UNET WindReference=Eulerian
UNET WindDragFormulation=Hsu (1988)
UNET D2 Coriolis=0
UNET D2 Cores= 0
UNET D2 Theta= 1
UNET D2 Theta Warmup= 1
UNET D2 Z Tol= 0.01
UNET D2 Volume Tol= 0.01
UNET D2 Max Iterations= 20
UNET D2 Equation= 0
UNET D2 RampUpFraction=0.1
UNET D2 TimeSlices= 1
UNET D2 Turbulence Formulation=Non-Conservative (original)
UNET D2 Eddy Viscosity=0.3
UNET D2 Transverse Eddy Viscosity=0.1
UNET D2 Smagorinsky Mixing=0
UNET D2 BCVolumeCheck=0
UNET D2 Cores=0
UNET D2 SolverType=PARDISO (Direct)
UNET D2 Minimum Iterations= 2147483647
UNET D2 Maximum Iterations= 2147483647
UNET D2 Restart Number= 10
UNET D2 Relaxation Coeff=1.3
UNET D2 SOR Precondition Iterations= 10
UNET D2 ILUT Maximum Fill= 8
UNET D2 ILUT Tolerance=1E-08
UNET D1D2 MaxIter= 0
UNET D1D2 ZTol=0.01
UNET D1D2 QTol=0.1
UNET D1D2 MinQTol=1
Write IC File= 0
Write IC File at Fixed DateTime=0
Write IC File at Sim End=0
Echo Input=False
Echo Parameters=False
Echo Output=False
Write Detailed= 0
HDF Write Warmup=0
HDF Write Time Slices=0
HDF Flush=0
HDF Compression= 1
HDF Chunk Size= 1
HDF Spatial Parts= 1
HDF Use Max Rows=0
HDF Fixed Rows= 1
Calibration Method= 0
Calibration Iterations= 20
Calibration Max Change=0.05
Calibration Tolerance=0.2
Calibration Maximum=1.5
Calibration Minimum=0.5
Calibration Optimization Method= 1
WQ AD Non Conservative
WQ ULTIMATE=-1
WQ Max Comp Step=1HOUR
WQ Output Interval=15MIN
WQ Output Selected Increments= 0
WQ Output face flow=0
WQ Output face velocity=0
WQ Output face area=0
WQ Output face dispersion=0
WQ Output cell volume=0
WQ Output cell surface area=0
WQ Output cell continuity=0
WQ Output cumulative cell continuity=0
WQ Output face conc=0
WQ Output face dconc_dx=0
WQ Output face courant=0
WQ Output face peclet=0
WQ Output face adv mass=0
WQ Output face disp mass=0
WQ Output cell mass=0
WQ Output cell source sink temp=0
WQ Output nsm pathways=0
WQ Output nsm derived pathways=0
WQ Create Restart=0
WQ Fixed Restart=0
WQ System Summary=0
WQ Write To DSS=0
Sorting and Armoring Iterations= 10
XS Update Threshold= 0.02
Bed Roughness Predictor= 0
Hydraulics Update Threshold= 0.02
Energy Slope Method= 1
Volume Change Method= 1
Sediment Retention Method= 0
Sediment TS Multiplier= 1
Warm Up Method= 0
XS Weighting Method= 0
Number of US Weighted Cross Sections= 1
Number of DS Weighted Cross Sections= 1
Upstream XS Weight=0
Main XS Weight=1
Downstream XS Weight=0
Number of DS XS's Weighted with US Boundary= 1
Upstream Boundary Weight= 1
Weight of XSs Associated with US Boundary= 0
Number of US XS's Weighted with DS Boundary= 1
Downstream Boundary Weight= 0.5
Weight of XSs Associated with DS Boundary= 0.5
Percentile Method= 0
Sediment Output Level= 3
Mass or Volume Output= 0
Output Increment Type= 1
Profile and TS Output Increment= 1
Transport Output Increment 1
XS Output Flag= 0
XS Output Increment= 10
Read HDF5 Sediment Hotstart= 0
Sediment Hotstart Type= 0
Write Gradation File= 0
Read Gradation Hotstart= 0
Write HDF5 File= 1
Write Binary Output= 1
Write DSS Sediment File= 0
DSS Sediment Output Type= 1
SV Curve= 0
Specific Gage Flag= 0
Subcell Erosion Methods= 0
Subcell Deposition Methods= 0
Advection Scheme= 1
Matrix Solver= 0
Implicit Weighting Factor= 1
Maximum Outer Loop Convergence Iterations= 5
Convergence Maximum Absolute= 0.001
Convergence RMSE= 0.0001
Grain Fractions Max Abs Error= 0.001
Max Subgrid Regions= 1
Max Subgrid Length Scale= 3.402823E+38
Initial Layer Thickness= 3.402823E+38
Min Layer Thickness= 3.402823E+38
Max Layer Thickness= 3.402823E+38
Number of Layers= 5

--- CHERRYFK.f01 (steady flow) ---

Flow Title=Flow
Program Version=6.20
Number of Profiles= 1
Profile Names=P100yr
River Rch & RM=CHERRYFK,Main,21182
     341
River Rch & RM=CHERRYFK,Main,13440
     661
River Rch & RM=CHERRYFK,Main,12378
     735
River Rch & RM=CHERRYFK,Main,7667
     846
Boundary for River Rch & Prof#=CHERRYFK,Main            , 1
Up Type= 0
Dn Type= 3
Dn Slope=0.002917
DSS Import GetInterval= 0
DSS Import GetPeak= 0
DSS Import FillOption= 0

--- CHERRYFK.g01 (geometry) ---

Geom Title=Geometry
Program Version=6.20

River Reach=CHERRYFK        ,Main
Reach XY= 30
2311704.34831186755384.8614436762310935.77989956754609.715340219
2310963.53044639754398.674837372     2310726.195      754385.949
     2310564.389      753849.491     2310731.403      753699.491
      2310410.57      753624.838      2310445.64      753225.879
     2310030.362      752930.046     2310039.737      751442.373
     2309355.818      750895.392     2309184.299       750426.46
     2308931.695       750588.44     2308774.408      750023.799
     2308482.128      750020.359     2307497.049      749228.736
     2307138.331      748375.158     2306974.567      748462.927
     2306882.496      748206.813     2306772.841       748388.44
     2306526.313      748301.634      2306189.23      747501.287
      2306176.19      747088.505     2306452.356      746838.143
2306176.67558133746432.089385277     2305834.711       746375.61
     2305820.757      745873.162     2305335.341      745402.328
     2305413.338       744628.25     2304930.287      744674.739

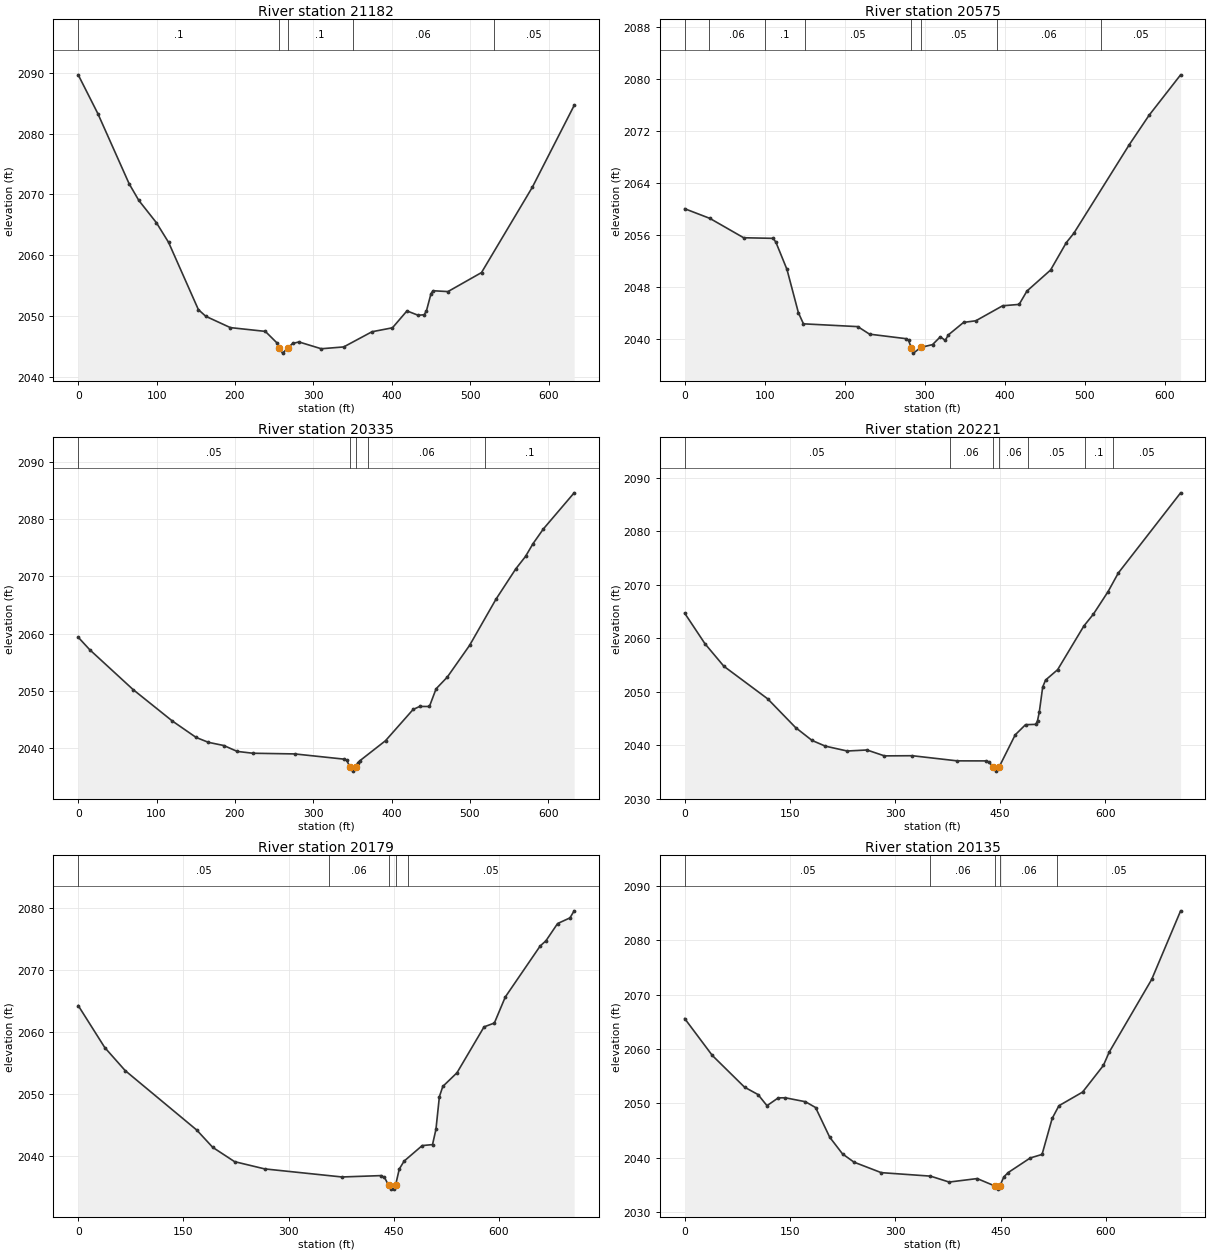
Type RM Length L Ch R = 1 ,21182   ,607.5,607.5,607.5
XS GIS Cut Line= 2
2311921.25298526755240.4149469092311388.67324035755581.916462726
#Sta/Elev= 30
       0 2089.67      25  2083.3      65 2071.73    77.3    2069    99.8 2065.32
   115.3 2062.09   153.3 2051.02   162.8 2049.92   194.1 2048.06   238.7 2047.44
   253.1  2045.6   256.1 2044.65   260.8 2043.86   267.4 2044.71   273.5 2045.45
   281.6  2045.7   310.1 2044.58   338.7 2044.88   374.8 2047.38   400.9 2048.03
   419.4 2050.81   433.7 2050.09   441.4 2050.18   444.3 2050.84   450.1 2053.66
   452.7 2054.13   471.7 2053.99   514.5 2057.12   579.4 2071.18   632.7 2084.63
#Mann= 5, -1 ,  0
       0     0.1       0   256.1   0.045       0   267.4     0.1       0
     350    0.06       0     530    0.05       0
Bank Sta=256.1,267.4
XS Rating Curve= 0 ,0
Exp/Cntr(USF)=0,0
Exp/Cntr=0.3,0.1

Type RM Length L Ch R = 1 ,20575   ,240.1,240.1,240.1
XS GIS Cut Line= 2
2311684.09915483754978.8681510642311179.97786957755339.341973316
#Sta/Elev= 30
       0 2060.06    31.5 2058.57    73.7 2055.59   110.6  2055.5     114  2054.9
   127.8 2050.72   142.1 2044.05   148.4 2042.34   216.3 2041.91     231 2040.75
   276.9 2040.05   279.7 2039.79   283.1 2038.69   285.9 2037.83     295 2038.71
   309.7 2039.14   319.5 2040.35   325.6 2039.78   329.4 2040.63   348.5 2042.56
   363.8 2042.81   397.3 2045.12   417.9 2045.33   427.7 2047.39   457.2 2050.62
   476.9 2054.85   486.2 2056.27   555.6 2069.93   580.2 2074.43   619.7 2080.67
#Mann= 8, -1 ,  0
       0    0.12       0      30    0.06       0     100     0.1       0
     150    0.05       0   283.1   0.045       0     295    0.05       0
     390    0.06       0     520    0.05       0
Bank Sta=283.1,295
XS Rating Curve= 0 ,0
Exp/Cntr(USF)=0,0
Exp/Cntr=0.3,0.1

Type RM Length L Ch R = 1 ,20335   ,114.3,114.3,114.3
XS GIS Cut Line= 2
2311579.75146944754812.1828873922311076.98534893755197.049675059
#Sta/Elev= 30
       0 2059.36    14.6 2057.19      70 2050.21   120.1 2044.71   150.6 2041.82
   166.2 2040.97   185.9 2040.41     203 2039.38     223 2039.06   276.5 2038.94
   339.9 2038.02   342.8 2037.83   347.1  2036.6   350.4 2035.93   354.2 2036.61
   357.1 2037.42   359.9 2037.78   392.4 2041.26   427.6 2046.72     436 2047.25
   448.4 2047.24   456.9 2050.33   471.2 2052.38   499.7 2057.94   533.4 2066.02
   558.6 2071.31   571.1  2073.5   580.7 2075.74   593.9 2078.31   633.2 2084.63
#Mann= 5, -1 ,  0
       0    0.05       0   347.1   0.045       0   354.2    0.05       0
     370    0.06       0     520     0.1       0
Bank Sta=347.1,354.2
XS Rating Curve= 0 ,0
Exp/Cntr(USF)=0,0
Exp/Cntr=0.3,0.1

Type RM Length L Ch R = 1 ,20221   ,41.5,41.5,41.5
XS GIS Cut Line= 4
2311574.33081046754748.4901443622311362.92511019754928.727055488
2311250.44643633754930.0822202332310991.60996998 755113.02946085
#Sta/Elev= 30
       0  2064.7    29.1 2058.96    55.9 2054.78   118.4 2048.69   158.1 2043.33
   181.6 2040.92   200.6 2039.85   231.8 2038.94     260 2039.13   284.9 2038.03
   324.6 2038.06   388.6  2037.1   430.3 2037.09   434.3 2036.88  439.012036.003
   444.2 2035.18   448.7 2036.02   471.4 2041.96   486.1 2043.86   500.8 2043.92
   503.2  2044.6   505.7 2046.17   510.6  2050.9   514.7  2052.2   531.9 2054.14
   569.4 2062.32   582.8  2064.5   603.7  2068.7   618.4  2072.2   707.3 2087.19
#Mann= 7, -1 ,  0
       0    0.05       0  377.81    0.06       0  439.01   0.045       0
   448.7    0.06       0   490.3    0.05       0   570.3     0.1       0
   610.3    0.05       0
Bank Sta=439.01,448.7
XS Rating Curve= 0 ,0
Exp/Cntr(USF)=0,0
Exp/Cntr=0.3,0.1

Type RM Length L Ch R = 1 ,20179   ,44.1,44.1,44.1
XS GIS Cut Line= 4
2311554.00333928754712.5782786112311342.59763901754892.815189737
2311230.11896515754894.170354483 2310971.2824988755077.117595099
#Sta/Elev= 30
       0  2064.3    37.9 2057.52      67 2053.81   169.1 2044.22   191.8 2041.44
     223 2039.13     266 2037.96   376.2 2036.66   431.9 2036.88   436.8 2036.59
   442.6 2035.33   446.6  2034.7   450.9 2034.72   452.7 2035.39   457.9 2037.94
   464.8 2039.22   490.6 2041.72   505.3 2041.88   510.2 2044.34   515.1 2049.61
     520 2051.26   540.2 2053.46   578.8 2060.86   593.5 2061.48   609.1 2065.68
   658.9 2073.91     667 2074.73   683.7 2077.52   701.3 2078.43   707.3 2079.57
#Mann= 5, -1 ,  0
       0    0.05       0  357.81    0.06       0   442.6   0.045       0
   452.7    0.06       0   470.3    0.05       0
Bank Sta=442.6,452.7
XS Rating Curve= 0 ,0
Exp/Cntr(USF)=0,0
Exp/Cntr=0.3,0.1

Type RM Length L Ch R = 1 ,20135   ,35,35,35
XS GIS Cut Line= 2
2311530.96553861754641.4321294832310944.17920389755034.429905622
#Sta/Elev= 30
       0 2065.59    39.3 2058.81    85.2 2052.98   104.5 2051.61   117.2 2049.57
   133.3 2051.01   143.3 2051.02   171.9  2050.3   186.4 2049.23   206.5 2043.78
   224.8  2040.7   241.1 2039.19   279.9 2037.26     350 2036.62   376.6 2035.53
   416.5 2036.17   441.5 2034.82   445.8 2034.23   448.7 2034.79   454.5 2036.48
   460.7 2037.28   492.1 2039.96   508.9 2040.61   523.3 2047.23   532.9 2049.56
   566.6 2052.07   596.2 2056.96   604.4 2059.39     665 2072.78   706.2 2085.39
#Mann= 5, -1 ,  0
       0    0.05       0     350    0.06       0   441.5   0.045       0
   448.7    0.06       0     530    0.05       0
Bank Sta=441.5,448.7
XS Rating Curve= 0 ,0
Exp/Cntr(USF)=0,0
Exp/Cntr=0.3,0.1

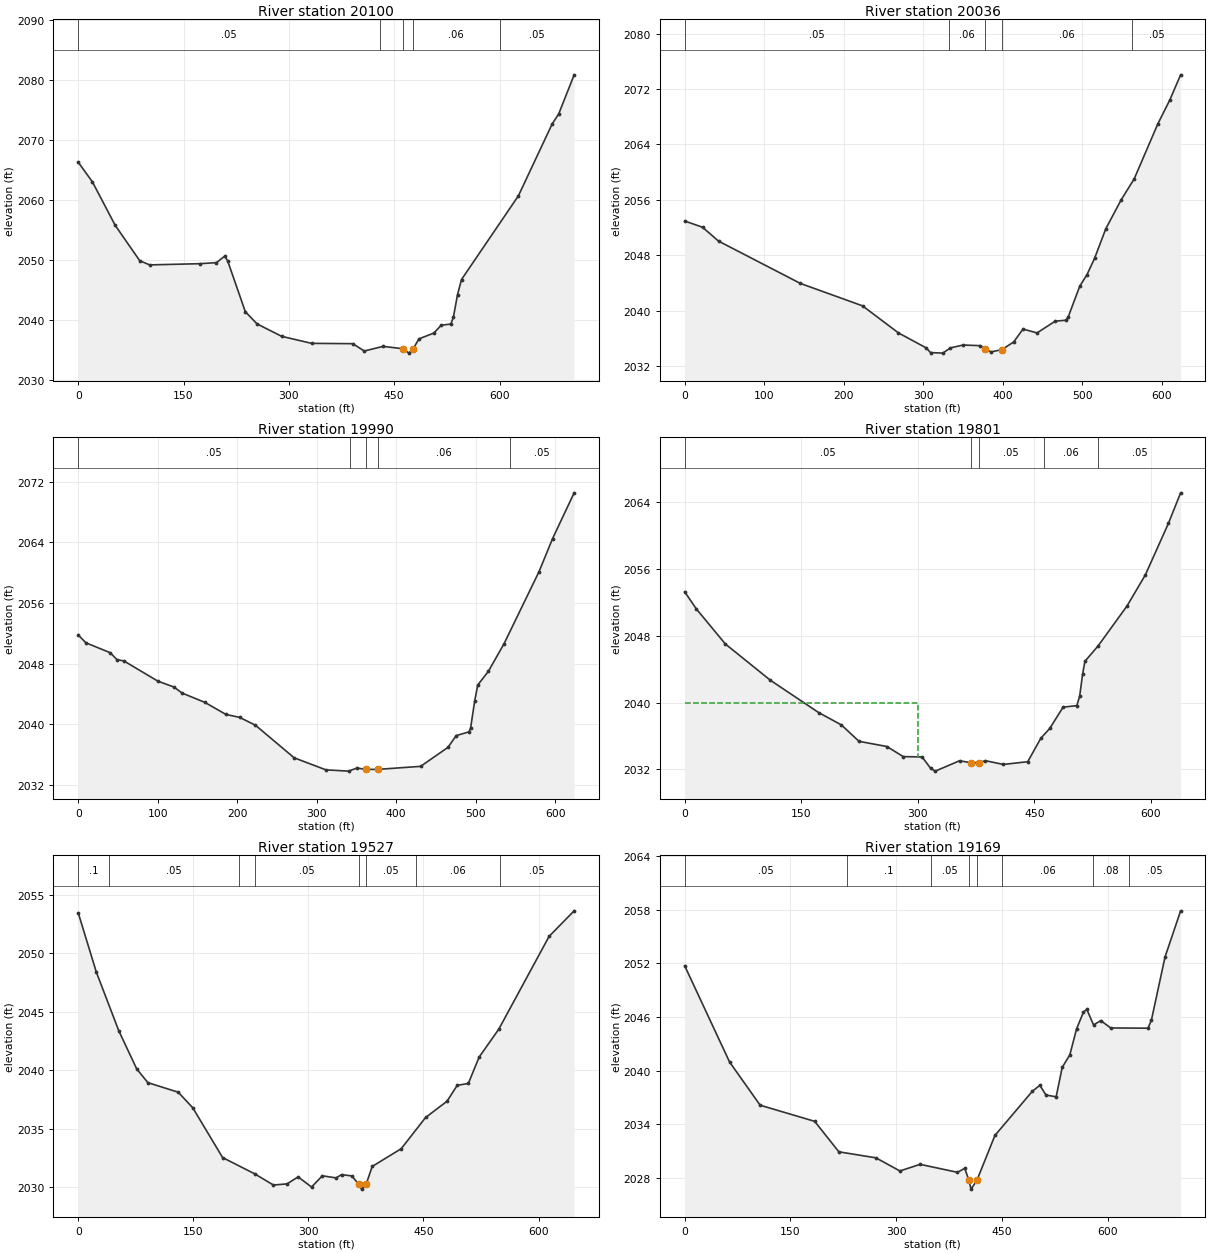
Type RM Length L Ch R = 1 ,20100   ,64,64,64
XS GIS Cut Line= 2
2311528.93279149754600.7771871242310942.14645677754993.774963263
#Sta/Elev= 30
       0  2066.3    20.2 2063.01    52.7 2055.75    87.6 2049.85   101.7 2049.15
   173.2 2049.35   196.9 2049.53   208.4 2050.59   212.7 2049.86   237.9 2041.35
   254.6  2039.3   289.8 2037.22   332.4 2036.05   390.9    2036   407.4 2034.77
   434.2 2035.55   463.1 2035.14   470.8 2034.42   476.6 2035.07   485.2  2036.8
   506.4 2037.77   516.9 2039.08   530.5 2039.27   534.2 2040.39   540.1 2044.17
   545.8 2046.71   626.8 2060.68   674.9 2072.68   684.2 2074.35   706.2 2080.88
#Mann= 5, -1 ,  0
       0    0.05       0     430    0.06       0   463.1   0.045       0
   476.6    0.06       0     600    0.05       0
Bank Sta=463.1,476.6
XS Rating Curve= 0 ,0
Exp/Cntr(USF)=0,0
Exp/Cntr=0.3,0.1

Type RM Length L Ch R = 1 ,20036   ,45.8,45.8,45.8
XS GIS Cut Line= 4
2311368.34576917754507.2708196972311173.20204585 754763.39695656
2311135.25743298754797.276075193   2310911.65525754911.109913799
#Sta/Elev= 30
       0 2052.94    22.5 2052.03    42.6 2050.03   145.5 2043.92   223.7 2040.68
   268.9 2036.77   303.9  2034.6   309.2 2033.93   324.7 2033.85   334.1  2034.6
   350.2 2035.02   371.6 2034.93   378.1  2034.4   385.3 2034.03   398.9 2034.35
   413.8 2035.46   425.6 2037.33   443.2 2036.77   466.1 2038.47   479.2  2038.6
   482.2 2039.01     497 2043.54     506 2045.18   515.5 2047.52   529.7 2051.82
     549 2055.99   565.4 2059.02   595.2 2066.98   610.1 2070.39   623.8 2074.05
#Mann= 5, -1 ,  0
       0    0.05       0     332    0.06       0   378.1   0.045       0
   398.9    0.06       0  562.86    0.05       0
Bank Sta=378.1,398.9
XS Rating Curve= 0 ,0
Exp/Cntr(USF)=0,0
Exp/Cntr=0.3,0.1

Type RM Length L Ch R = 1 ,19990   ,189.5,189.5,189.5
XS GIS Cut Line= 4
 2311352.7613746754473.3917010652311157.61765128754729.517837928
2311119.67303841 754763.396956562310896.07085543754877.230795166
#Sta/Elev= 30
       0 2051.77     9.8 2050.73    40.2 2049.43    48.8 2048.51    57.3 2048.35
   100.3 2045.67   120.4  2044.9   130.5 2044.11   159.4 2042.87   185.8 2041.28
   202.9  2040.9   222.9 2039.86   271.6 2035.56   311.5 2033.97     340  2033.8
   350.7 2034.21   361.5 2034.03   376.8 2034.03   430.7 2034.43     465 2036.93
   475.5 2038.49   491.4 2038.98   493.5 2039.45   498.7 2043.05   502.5 2045.16
   515.9 2046.97   535.5 2050.59   579.6 2060.12   596.7  2064.5   623.8 2070.53
#Mann= 5, -1 ,  0
       0    0.05       0     342    0.06       0   361.5   0.045       0
   376.8    0.06       0  542.86    0.05       0
Bank Sta=361.5,376.8
XS Rating Curve= 0 ,0
Exp/Cntr(USF)=0,0
Exp/Cntr=0.3,0.1

Type RM Length L Ch R = 1 ,19801   ,273.8,273.8,273.8
XS GIS Cut Line= 3
2311346.66313325754457.1297241212311132.54710349754515.401808169
2310849.31767172754820.313875863
#Sta/Elev= 30
       0 2053.28      15 2051.23    52.3 2047.03   110.4 2042.67   172.5  2038.8
   201.6 2037.33   224.3 2035.36   260.2 2034.74   281.2 2033.53   305.5 2033.49
   316.5 2032.12   322.4 2031.79   353.6 2033.03   367.8 2032.81  378.342032.806
     387 2033.04     410 2032.59   441.4 2032.92   458.3 2035.74   469.7  2036.9
   486.9 2039.46   504.6 2039.64   508.2 2040.77   512.1 2043.48     515 2044.95
   531.9 2046.79   569.2 2051.59   592.7  2055.3   622.5  2061.5   638.1 2065.14
#Mann= 5, -1 ,  0
       0    0.05       0   367.8   0.045       0  378.34    0.05       0
   461.9    0.06       0   531.9    0.05       0
#XS Ineff= 2 , 0
             300    2040
Permanent Ineff=
       F       F
Bank Sta=367.8,378.34
XS Rating Curve= 0 ,0
Exp/Cntr(USF)=0,0
Exp/Cntr=0.3,0.1

Type RM Length L Ch R = 1 ,19527   ,358,358,358
XS GIS Cut Line= 2
2311246.38094209754327.0339085712310689.40823177754654.983776936
#Sta/Elev= 30
       0 2053.47    23.6  2048.4    52.8 2043.39    76.2 2040.12    90.8 2038.94
   130.4 2038.12   149.3 2036.79   188.2 2032.53     230 2031.14   254.4 2030.18
   272.3 2030.28   286.6 2030.88   304.1 2030.01   318.2 2030.97   336.2 2030.79
   343.2 2031.07   356.7 2030.96   365.5 2030.25   369.3 2029.83  375.222030.237
   383.2 2031.77     421 2033.29   452.8 2035.96   480.7 2037.35     494 2038.71
   508.5 2038.87   522.5 2041.12   548.2 2043.52   613.8 2051.46   646.4 2053.64
#Mann= 8, -1 ,  0
       0     0.1       0      40    0.05       0     210     0.1       0
     230    0.05       0   365.5   0.045       0  375.22    0.05       0
     440    0.06       0     550    0.05       0
Bank Sta=365.5,375.22
XS Rating Curve= 0 ,0
Exp/Cntr(USF)=0,0
Exp/Cntr=0.3,0.1

Type RM Length L Ch R = 1 ,19169   ,350.9,350.9,350.9
XS GIS Cut Line= 2
 2311156.9400689754190.1622692952310573.85385822754584.189201288
#Sta/Elev= 30
       0 2051.73    63.7 2040.97   107.1 2036.14   184.4 2034.34   218.8 2030.93
   271.3 2030.26   305.4 2028.79     334 2029.53   387.1 2028.64   397.4 2029.09
   403.2 2027.75   406.4 2026.76   414.7 2027.75   440.2 2032.76   493.3  2037.7
     504 2038.37   512.6 2037.28   527.1 2037.08   535.7 2040.37   546.5 2041.77
   556.1 2044.68   565.8 2046.54   570.6 2046.85   580.2 2045.11   590.4  2045.6
   604.4 2044.78   657.5 2044.75   662.3 2045.67   681.6 2052.71   703.7 2057.87
#Mann= 8, -1 ,  0
       0    0.05       0     230     0.1       0     350    0.05       0
   403.2   0.045       0   414.7    0.05       0     450    0.06       0
     580    0.08       0     630    0.05       0
Bank Sta=403.2,414.7
XS Rating Curve= 0 ,0
Exp/Cntr(USF)=0,0
Exp/Cntr=0.3,0.1

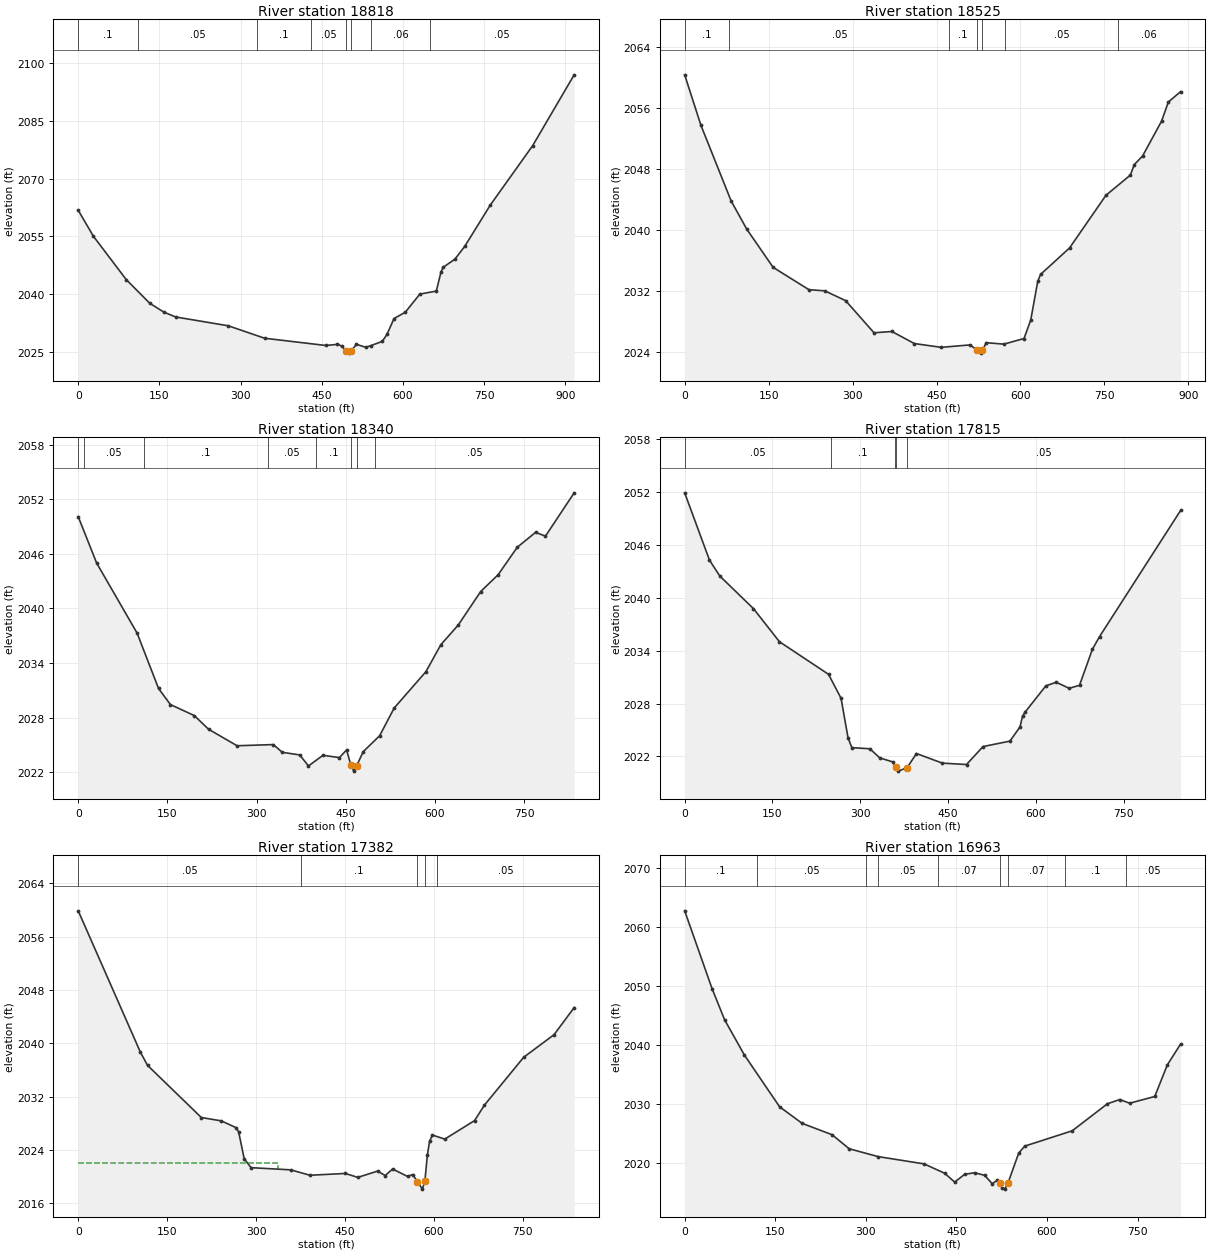
Type RM Length L Ch R = 1 ,18818   ,292.6,292.6,292.6
XS GIS Cut Line= 2
2311170.16535811754100.5123086212310325.33199516754454.806956626
#Sta/Elev= 30
       0 2061.77    28.2 2055.01    88.9 2043.78   132.3 2037.65   158.3 2035.37
     180 2034.12   277.1 2031.84   344.3 2028.61   457.4 2026.73   478.8 2027.02
     488 2026.55     494 2025.25   500.1 2024.75   503.2  2025.2     514 2027.03
   531.3 2026.25     540 2026.67   561.7 2027.79   570.4 2029.61   583.4 2033.72
   604.1 2035.34   631.1 2040.05   661.5 2040.83   670.1 2045.74     674 2046.98
   695.7 2049.08   714.1 2052.44   761.2 2063.12   839.4  2078.5   916.1 2096.87
#Mann= 8, -1 ,  0
       0     0.1       0     110    0.05       0     330     0.1       0
     430    0.05       0     494   0.045       0   503.2    0.05       0
     540    0.06       0     650    0.05       0
Bank Sta=494,503.2
XS Rating Curve= 0 ,0
Exp/Cntr(USF)=0,0
Exp/Cntr=0.3,0.1

Type RM Length L Ch R = 1 ,18525   ,185.9,185.9,185.9
XS GIS Cut Line= 4
2311144.11808134754032.0269798442310987.49210055754076.823896471
2310526.73902722754087.8598982272310285.63707823754191.411961076
#Sta/Elev= 30
       0 2060.39    29.1 2053.75    83.1 2043.82   110.9 2040.14     158 2035.12
   222.2 2032.18   250.2 2032.04   287.6 2030.75   338.3 2026.53   370.3  2026.7
   410.3 2025.12   458.3 2024.62   510.3 2024.94   522.6 2024.23   530.3 2023.86
  531.892024.222     539 2025.23   570.3 2025.04   606.4 2025.78   618.4 2028.21
   630.9 2033.28   635.9 2034.19   687.7 2037.66   752.8 2044.58   796.4 2047.23
   803.4 2048.61   818.1 2049.72   852.1  2054.3   864.3 2056.82   886.2 2058.19
#Mann= 7, -1 ,  0
       0     0.1       0      80    0.05       0  472.91     0.1       0
   522.6   0.045       0  531.89     0.1       0  572.91    0.05       0
  773.79    0.06       0
Bank Sta=522.6,531.89
XS Rating Curve= 0 ,0
Exp/Cntr(USF)=0,0
Exp/Cntr=0.3,0.1

Type RM Length L Ch R = 1 ,18340   ,524.3,524.3,524.3
XS GIS Cut Line= 3
2311075.16712574 753936.032918422310521.78890905753959.610436424
2310254.11473406754042.825205851
#Sta/Elev= 30
       0 2050.09      31 2044.99    99.1 2037.28   135.1  2031.2   155.1 2029.43
   195.2 2028.22   219.2 2026.72   267.2  2024.9   328.1 2025.03   343.3 2024.18
   372.6 2023.89   387.3 2022.68   411.7 2023.85   439.4  2023.6   451.4 2024.44
  458.562022.797   463.4 2022.11   468.52022.722   479.4 2024.25     507    2026
   531.5 2029.05   584.9 2033.05     610 2036.01   639.3 2038.18     677 2041.86
   706.4 2043.71   738.6 2046.73   769.2 2048.36     786 2047.95   834.2 2052.71
#Mann= 8, -1 ,  0
       0     0.1       0      10    0.05       0     110     0.1       0
     320    0.05       0     400     0.1       0  458.56   0.045       0
   468.5     0.1       0     500    0.05       0
Bank Sta=458.56,468.5
XS Rating Curve= 0 ,0
Exp/Cntr(USF)=0,0
Exp/Cntr=0.3,0.1

Type RM Length L Ch R = 1 ,17815   ,433,433,433
XS GIS Cut Line= 2
 2310998.5281023 753531.921309752310231.83656967753893.113458853
#Sta/Elev= 30
       0 2051.94    42.4 2044.29    60.1 2042.48   117.6 2038.78     162 2035.02
   245.8 2031.32   267.2  2028.6   279.2 2024.09   285.6 2022.99   316.5 2022.86
   333.3 2021.83   356.3 2021.35   360.4 2020.74   365.2 2020.32  380.242020.726
   396.1 2022.32   440.3 2021.23   481.6 2021.07   509.8 2023.11   555.8 2023.73
     573 2025.34   577.4 2026.57   581.8 2027.03   617.2 2030.01   634.9 2030.42
     657 2029.73   674.7 2030.07   696.8 2034.17     709 2035.61   847.5 2049.94
#Mann= 5, -1 ,  0
       0    0.05       0     250     0.1       0     360    0.05       0
   360.4   0.045       0  380.24    0.05       0
Bank Sta=360.4,380.24
XS Rating Curve= 0 ,0
Exp/Cntr(USF)=0,0
Exp/Cntr=0.3,0.1

Type RM Length L Ch R = 1 ,17382   ,418.9,418.9,418.9
XS GIS Cut Line= 3
2310953.00459506753429.838293503 2310772.2900663753502.951805139
2310159.86564984753693.649290237
#Sta/Elev= 30
       0 2059.85   104.9 2038.65   116.9 2036.68   207.6 2028.86   241.5 2028.35
   266.3 2027.33   270.5 2026.72   279.9  2022.7   291.4 2021.34   358.5 2021.01
   390.8  2020.2   450.6 2020.47   471.5 2019.88   505.1 2020.83   517.7 2020.15
   530.2 2021.14   555.4 2020.02   564.2 2020.31   572.1 2019.23   580.5 2018.12
   584.7 2019.39   588.9 2023.26   592.6 2025.31   597.3 2026.23   618.2 2025.62
   668.5  2028.4   685.2 2030.73   751.4  2037.9   802.5 2041.28   836.4 2045.34
#Mann= 5, -1 ,  0
       0    0.05       0  374.94     0.1       0   572.1   0.045       0
   584.7     0.1       0  604.94    0.05       0
#XS Ineff= 2 , 0
          337.51    2022
Permanent Ineff=
       F       F
Bank Sta=572.1,584.7
XS Rating Curve= 0 ,0
Exp/Cntr(USF)=0,0
Exp/Cntr=0.3,0.1

Type RM Length L Ch R = 1 ,16963   ,444.8,444.8,444.8
XS GIS Cut Line= 2
2310884.02958408753283.6112702322310090.81695784753496.054304042
#Sta/Elev= 30
       0 2062.72    45.4 2049.51    66.1 2044.25    98.8 2038.28   157.2 2029.49
   194.5 2026.68   244.2 2024.75   272.3 2022.38     320 2021.05   396.4 2019.81
   430.5 2018.22   447.1 2016.72   463.6 2018.04   480.2 2018.31   496.8 2017.87
   509.2 2016.44   517.5 2017.04   521.6 2016.63   525.8 2015.66   529.9 2015.53
  535.592016.632   553.1 2021.64     563 2022.82   641.7 2025.42   700.1 2030.01
   720.4 2030.72   736.9  2030.1   778.4 2031.24   799.1 2036.58   821.2 2040.13
#Mann= 9, -1 ,  0
       0     0.1       0     120    0.05       0     300     0.1       0
     320    0.05       0     420    0.07       0   521.6   0.045       0
  535.59    0.07       0     630     0.1       0     730    0.05       0
Bank Sta=521.6,535.59
XS Rating Curve= 0 ,0
Exp/Cntr(USF)=0,0
Exp/Cntr=0.3,0.1

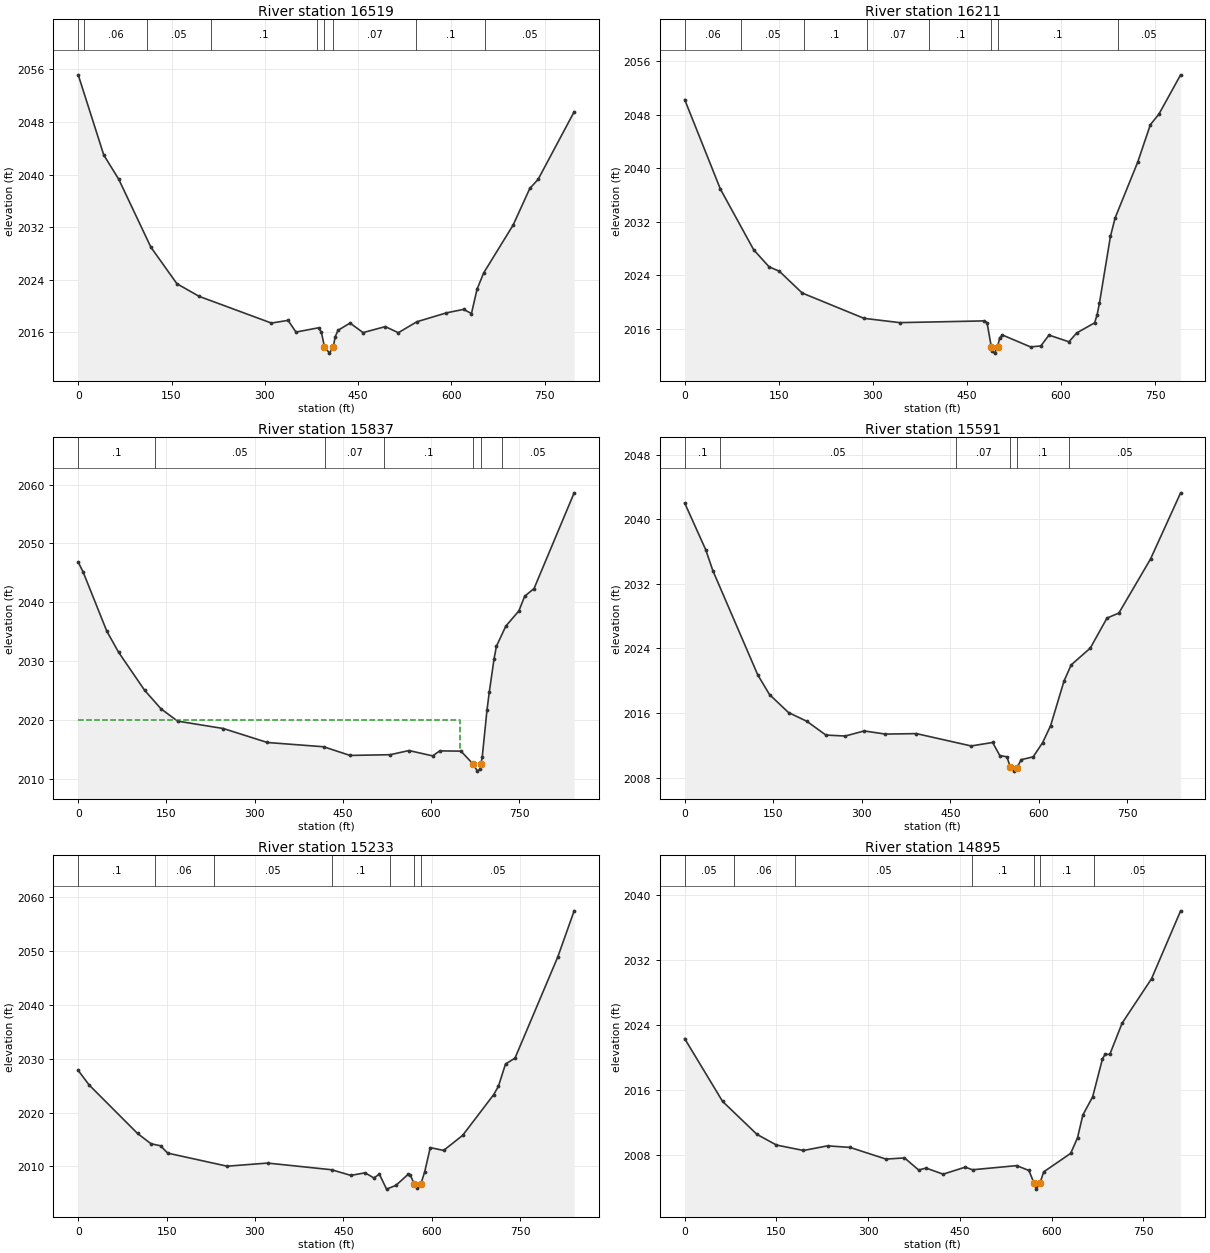
Type RM Length L Ch R = 1 ,16519   ,307.2,307.2,307.2
XS GIS Cut Line= 3
2310784.70556827753039.4397313722310632.96054412753061.511734884
2310056.32945235 753348.44778055
#Sta/Elev= 30
       0 2055.15    41.1 2042.96    65.2 2039.27   116.8 2028.96   158.7  2023.4
   194.4 2021.48   310.6 2017.42   337.4 2017.83   350.1 2016.05   386.4  2016.7
     391    2016   395.9 2013.83     404 2012.85   410.2 2013.84   413.2 2015.35
   417.8 2016.32   437.1 2017.42     458 2015.97   493.8 2016.88   514.7 2015.95
   544.5 2017.62   592.1 2018.97   619.5  2019.5   632.3 2018.87   641.2 2022.54
   651.9 2025.04   699.3 2032.32   726.1 2037.88   739.5 2039.27   797.4 2049.53
#Mann= 9, -1 ,  0
       0     0.1       0      10    0.06       0     110    0.05       0
  213.34     0.1       0  383.34    0.07       0   395.9   0.045       0
   410.2    0.07       0  543.34     0.1       0  653.34    0.05       0
Bank Sta=395.9,410.2
XS Rating Curve= 0 ,0
Exp/Cntr(USF)=0,0
Exp/Cntr=0.3,0.1

Type RM Length L Ch R = 1 ,16211   ,374.8,374.8,374.8
XS GIS Cut Line= 2
2310759.87456432752974.6032210532309985.97494116 753136.00474674
#Sta/Elev= 30
       0 2050.23    56.9 2036.88     110 2027.82   134.5 2025.28   150.9 2024.62
   187.3 2021.37   285.9 2017.59   342.9 2016.95   477.8 2017.21     482 2016.95
   488.8 2013.34     490 2012.65   494.1  2012.4   498.9 2013.38   502.2  2014.7
   506.4 2015.11   551.3 2013.33   567.7 2013.47   580.8 2015.09   612.6 2014.09
   624.9 2015.41   653.5 2016.92   657.5 2018.12   661.2 2019.86   678.7 2029.81
   686.2 2032.58   722.1 2040.87   742.4 2046.49   755.9 2048.04   790.6 2053.92
#Mann= 8, -1 ,  0
       0    0.06       0      90    0.05       0     190     0.1       0
     290    0.07       0     390     0.1       0   488.8   0.045       0
   498.9     0.1       0     690    0.05       0
Bank Sta=488.8,498.9
XS Rating Curve= 0 ,0
Exp/Cntr(USF)=0,0
Exp/Cntr=0.3,0.1

Type RM Length L Ch R = 1 ,15837   ,245.5,245.5,245.5
XS GIS Cut Line= 2
2310700.55605488752844.9302004162309860.44042118752919.423212271
#Sta/Elev= 30
       0 2046.82     8.4 2045.13    48.6 2035.09    68.6 2031.51   112.8 2025.05
   140.9 2021.87     169 2019.79   246.9 2018.53   321.6 2016.16   417.4 2015.43
   462.2 2013.96   530.5 2014.08   562.6 2014.79   602.7 2013.88   614.8 2014.73
   650.9 2014.69     671 2012.55     679 2011.29   683.1 2011.62  684.732012.494
   687.1 2013.69   695.1  2021.6   699.1 2024.75   707.1 2030.31   711.2 2032.52
   727.2 2035.94   749.4 2038.53   759.3 2041.03   775.2 2042.33   843.4  2058.6
#Mann= 7, -1 ,  0
       0     0.1       0     130    0.05       0     420    0.07       0
     520     0.1       0     671   0.045       0  684.73     0.1       0
     720    0.05       0
#XS Ineff= 2 , 0
             650    2020
Permanent Ineff=
       F       F
Bank Sta=671,684.73
XS Rating Curve= 0 ,0
Exp/Cntr(USF)=0,0
Exp/Cntr=0.3,0.1

Type RM Length L Ch R = 1 ,15591   ,357.6,357.6,357.6
XS GIS Cut Line= 3
2310635.82912921752630.1290619712310295.90903864752646.973002635
2309800.48603513752713.062001317
#Sta/Elev= 30
       0 2042.03    35.7 2036.23    47.7 2033.65   123.8 2020.73   143.8 2018.28
   175.9 2016.06   207.1 2014.97   239.2 2013.27     272 2013.15   304.1 2013.78
   340.1 2013.39   392.5 2013.45   485.3 2011.92   521.7 2012.35   533.8 2010.73
   545.9 2010.57   551.7 2009.26     558  2008.8   562.8 2009.22   570.1 2010.22
   590.3 2010.57   606.4 2012.34   619.8 2014.42   642.7 2019.99   654.8 2021.97
   687.1 2024.05   715.4 2027.77   735.5 2028.39   789.2  2035.1   840.1 2043.29
#Mann= 6, -1 ,  0
       0     0.1       0      60    0.05       0  460.34    0.07       0
   551.7   0.045       0   562.8     0.1       0  650.34    0.05       0
Bank Sta=551.7,562.8
XS Rating Curve= 0 ,0
Exp/Cntr=0.3,0.1

Type RM Length L Ch R = 1 ,15233   ,338.4,338.4,338.4
XS GIS Cut Line= 2
 2310606.5545419752330.0039096442309772.72329809752444.962261273
#Sta/Elev= 30
       0 2027.84    18.6 2025.13   100.7 2016.13   123.5 2014.22   139.7 2013.84
   151.8 2012.48   252.7 2010.05   321.4 2010.63     430 2009.39   462.7 2008.34
   486.9 2008.82   501.7 2007.87   511.2 2008.56   523.3 2005.79   539.4  2006.5
   559.6 2008.51   563.7 2008.38   570.52006.712   575.8 2005.93  581.172006.655
   587.9 2008.94   597.5  2013.5   620.2 2012.98   652.5 2015.78     705 2023.32
   713.1 2024.87   725.2 2029.03   741.3 2030.12     814 2048.94   841.7 2057.48
#Mann= 7, -1 ,  0
       0     0.1       0     130    0.06       0     230    0.05       0
     430     0.1       0     530    0.05       0   570.5   0.045       0
  581.17    0.05       0
Bank Sta=570.5,581.17
XS Rating Curve= 0 ,0
Exp/Cntr(USF)=0,0
Exp/Cntr=0.3,0.1

Type RM Length L Ch R = 1 ,14895   ,414.2,414.2,414.2
XS GIS Cut Line= 2
2310553.99423919752113.9136693512309744.68744372752164.495344068
#Sta/Elev= 30
       0 2022.33    61.9 2014.62   118.2 2010.56   150.1 2009.25   194.2 2008.58
   233.6 2009.15   270.3 2008.96   329.2 2007.52   359.4 2007.67   382.6 2006.18
   394.6 2006.42   422.6 2005.67   458.7 2006.53   470.7 2006.21   542.9 2006.72
   562.9 2006.12   571.3 2004.54   574.9 2003.83  580.742004.534     587 2005.95
   631.2 2008.23   642.3 2010.14   651.1 2012.95   667.1 2015.18   683.1 2019.84
   687.2 2020.38   695.2 2020.41   715.2 2024.23   763.3 2029.69   810.9 2038.04
#Mann= 7, -1 ,  0
       0    0.05       0      80    0.06       0     180    0.05       0
     470     0.1       0   571.3   0.045       0  580.74     0.1       0
     670    0.05       0
Bank Sta=571.3,580.74
XS Rating Curve= 0 ,0
Exp/Cntr(USF)=0,0
Exp/Cntr=0.3,0.1

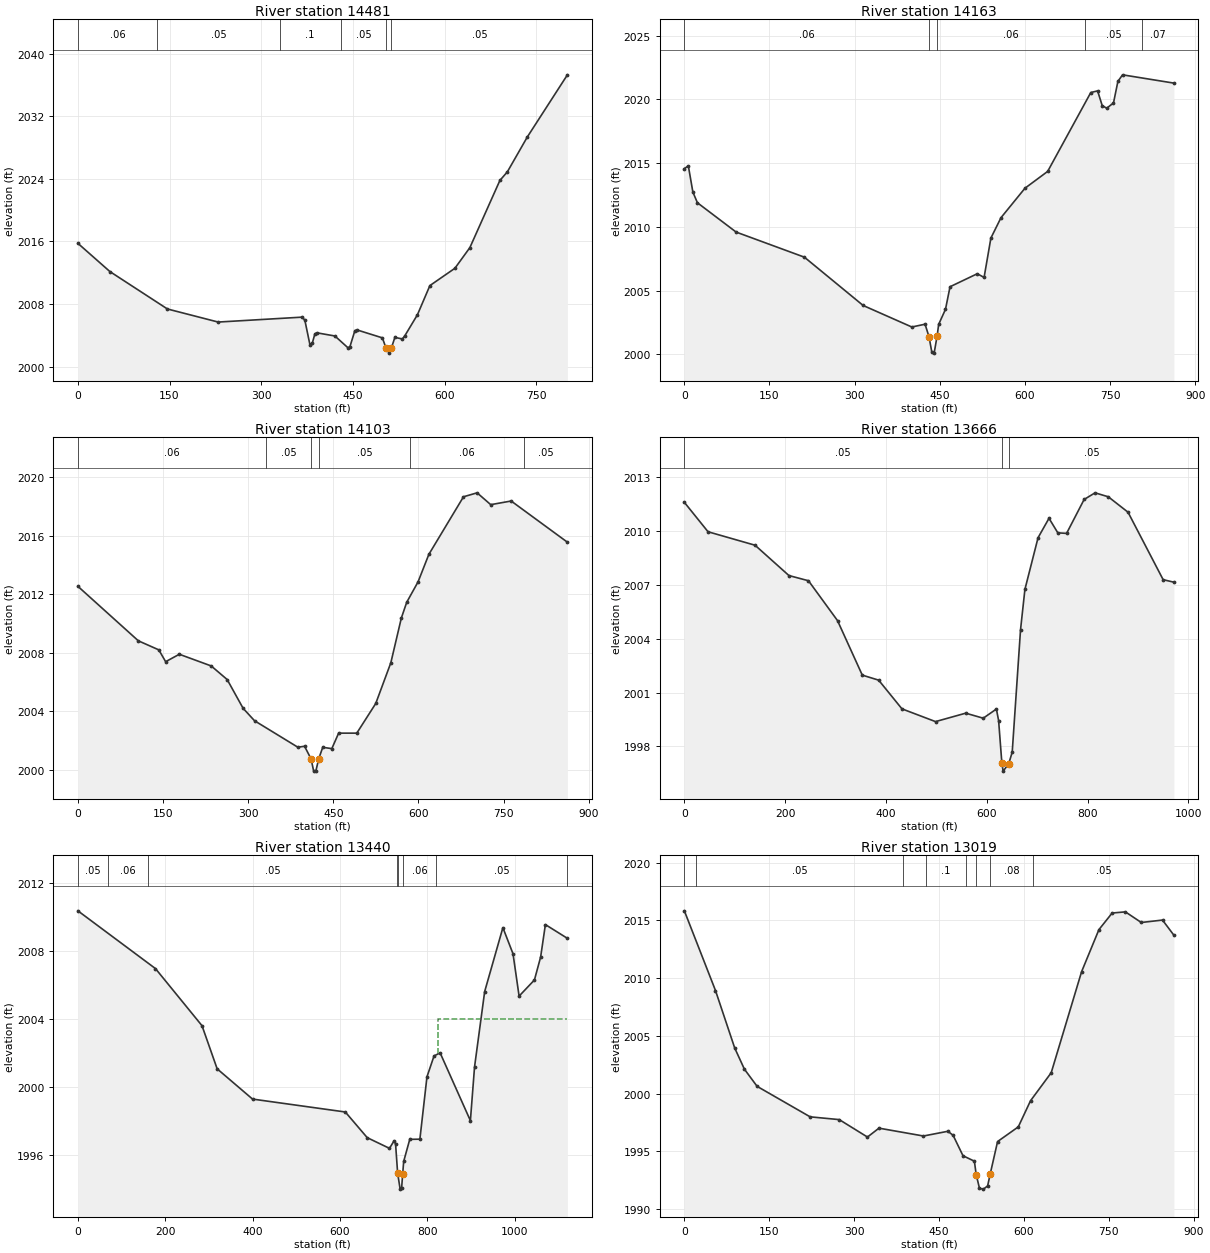
Type RM Length L Ch R = 1 ,14481   ,317.9,317.9,317.9
BEGIN DESCRIPTION:
Structure XS 4
END DESCRIPTION:
XS GIS Cut Line= 2
2310503.41256447751792.0302847912309720.16299537751959.103089158
#Sta/Elev= 30
       0 2015.75    52.4 2012.14   146.5 2007.36   229.5 2005.69   367.3 2006.32
   371.4  2005.9   379.6 2002.81   383.7 2003.05   387.8 2004.19   391.4 2004.31
   420.5 2003.91   441.9  2002.4     445 2002.52   453.2  2004.6   457.3 2004.67
   498.2 2003.67     504 2002.38   509.3 2001.72   512.7 2002.32   518.6 2003.73
   530.9 2003.53     535 2003.95   555.5 2006.62   575.9 2010.35   616.8 2012.56
   641.3  2015.2   690.4 2023.78   702.7 2024.89   735.4 2029.35   800.9 2037.28
#Mann= 6, -1 ,  0
       0    0.06       0     130    0.05       0     330     0.1       0
     430    0.05       0     504   0.045       0   512.7    0.05       0
Bank Sta=504,512.7
XS Rating Curve= 0 ,0
Exp/Cntr(USF)=0,0
Exp/Cntr=0.3,0.1

Type RM Length L Ch R = 1 ,14163   ,59.6,59.6,59.6
BEGIN DESCRIPTION:
Structure XS 3
END DESCRIPTION:
XS GIS Cut Line= 5
2310491.13788566751672.3988713052310330.19619338751661.669425153
2310137.06616264751644.808866914 2309936.2722418751643.276088892
2309629.71663745751646.341644935
#Sta/Elev= 30
       0 2014.57       7 2014.79      15 2012.73      23 2011.89    91.2 2009.59
   211.5 2007.62     315 2003.83   400.8 2002.14   424.1 2002.36   431.1 2001.37
   436.1 2000.14   440.1 2000.09  445.27 2001.41   448.1 2002.35   460.1 2003.53
   468.1  2005.3   516.1 2006.32   528.1 2006.03   540.1 2009.12   557.9 2010.72
   600.1 2013.03   640.1 2014.35   716.1 2020.54   728.1 2020.67   736.2 2019.52
   744.1 2019.31   756.1 2019.72   763.9 2021.42   772.1 2021.93   862.5 2021.28
#Mann= 5, -1 ,  0
       0    0.06       0   431.1   0.045       0  445.27    0.06       0
  705.96    0.05       0  805.96    0.07       0
Bank Sta=431.1,445.27
XS Rating Curve= 0 ,0
Exp/Cntr(USF)=0,0
Exp/Cntr=0.3,0.1

Type RM Length L Ch R = 1 ,14103   ,437.7,437.7,437.7
BEGIN DESCRIPTION:
Structure XS 2
END DESCRIPTION:
XS GIS Cut Line= 5
2310474.44896379751612.6792332992310313.50727151751601.949787147
2310120.37724077751585.0892289082309919.58331993751583.556450886
2309613.02771558751586.622006929
#Sta/Elev= 30
       0 2012.54   106.5 2008.81   142.6 2008.19   154.6 2007.38   178.7 2007.89
   234.9 2007.09     263 2006.16   291.1 2004.19   311.2 2003.34   387.4 2001.53
   399.4 2001.59   410.9 2000.72   415.4 1999.89   419.4 1999.92   424.4 2000.74
   431.4 2001.52   447.4 2001.43   459.4 2002.49   491.4 2002.49   524.8 2004.52
   551.4 2007.31   569.9 2010.37   579.4 2011.45   599.4 2012.85   618.4 2014.73
   679.4 2018.67   703.4 2018.94   727.4 2018.13   763.4 2018.38   862.5 2015.56
#Mann= 6, -1 ,  0
       0    0.06       0   331.3    0.05       0   410.9   0.045       0
   424.4    0.05       0  585.96    0.06       0  785.96    0.05       0
Bank Sta=410.9,424.4
XS Rating Curve= 0 ,0
Exp/Cntr(USF)=0,0
Exp/Cntr=0.3,0.1

Type RM Length L Ch R = 1 ,13666   ,225.8,225.8,225.8
BEGIN DESCRIPTION:
Structure XS 1
END DESCRIPTION:
XS GIS Cut Line= 3
2310440.41682117751521.0229595552310068.39318682751301.891177322
2309572.58653867751514.921012144
#Sta/Elev= 30
       0  2011.6      47 2009.96   140.3 2009.21   207.5 2007.52   246.3 2007.23
   303.9 2005.01   353.1 2001.97   385.6 2001.69   431.8 2000.09   498.4 1999.38
   558.3 1999.85   593.1 1999.57   619.2 2000.08   623.6 1999.44630.06131997.065
   632.6 1996.62643.76051997.038   650.6 1997.68   667.1  2004.5   675.8 2006.75
   701.9 2009.63   723.6 2010.71   741.1  2009.9   758.5 2009.87   793.3 2011.76
     815 2012.13   841.2 2011.91   880.4 2011.05   950.1 2007.29   971.4 2007.15
#Mann= 3, -1 ,  0
       0    0.05       0630.0613   0.045       0643.7605    0.05       0
Bank Sta=630.0613,643.7605
XS Rating Curve= 0 ,0
Exp/Cntr(USF)=0,0
Exp/Cntr=0.3,0.1

Type RM Length L Ch R = 1 ,13440   ,421.3,421.3,421.3
XS GIS Cut Line= 3
2310420.41370868751418.1261208192309851.64461538751145.999528764
2309428.74518178751393.610211625
#Sta/Elev= 30
       0 2010.39   177.6 2006.99   284.1 2003.63   318.8 2001.09   399.8 1999.31
   612.2 1998.55   662.3 1997.04   713.3 1996.41   723.9 1996.86   727.2 1996.68
     732 1994.94   737.7 1994.01   741.1 1994.08   743.5  1994.9   745.8 1995.64
   759.7 1996.94   782.9 1996.95   799.1 2000.62   815.3 2001.85   829.2 2002.03
   898.5 1998.04     908  2001.2   931.2 2005.64   972.9  2009.4   996.1 2007.86
    1010 2005.37  1045.1 2006.32  1059.3 2007.67  1070.2 2009.58  1120.6 2008.77
#Mann= 8, -1 ,  0
       0    0.05       0      70    0.06       0     160    0.05       0
  730.52    0.06       0     732   0.045       0   743.5    0.06       0
  820.52    0.05       0 1120.52    0.06       0
#XS Ineff= 2 , 0
                             825            2004
Permanent Ineff=
       F       F
Bank Sta=732,743.5
XS Rating Curve= 0 ,0
Exp/Cntr(USF)=0,0
Exp/Cntr=0.3,0.1

Type RM Length L Ch R = 1 ,13019   ,178.2,178.2,178.2
XS GIS Cut Line= 3
2309839.70776111750594.8928435592309749.03228184 750683.77115292
2309365.21304987751314.359510368
#Sta/Elev= 30
       0 2015.82      55 2008.92      89 2003.94   106.1 2002.11   128.6 2000.62
   222.3 1997.98   273.8 1997.74   323.6 1996.23     344    1997   422.6 1996.32
   465.8 1996.73     475 1996.38   492.5 1994.61   512.6 1994.14   515.8 1992.98
   521.6 1991.79   528.7 1991.72     536    1992   540.7 1993.06   553.6 1995.84
   590.2 1997.11   611.8 1999.37   648.4  2001.8   702.1 2010.55   732.7 2014.19
   756.1 2015.63   779.5 2015.73   807.6 2014.81   845.1 2015.02   865.2 2013.71
#Mann= 8, -1 ,  0
       0     0.1       0      20    0.05       0  386.97    0.08       0
  426.97     0.1       0  496.97    0.08       0   515.8   0.045       0
   540.7    0.08       0  616.97    0.05       0
Bank Sta=515.8,540.7
XS Rating Curve= 0 ,0
Exp/Cntr=0.3,0.1