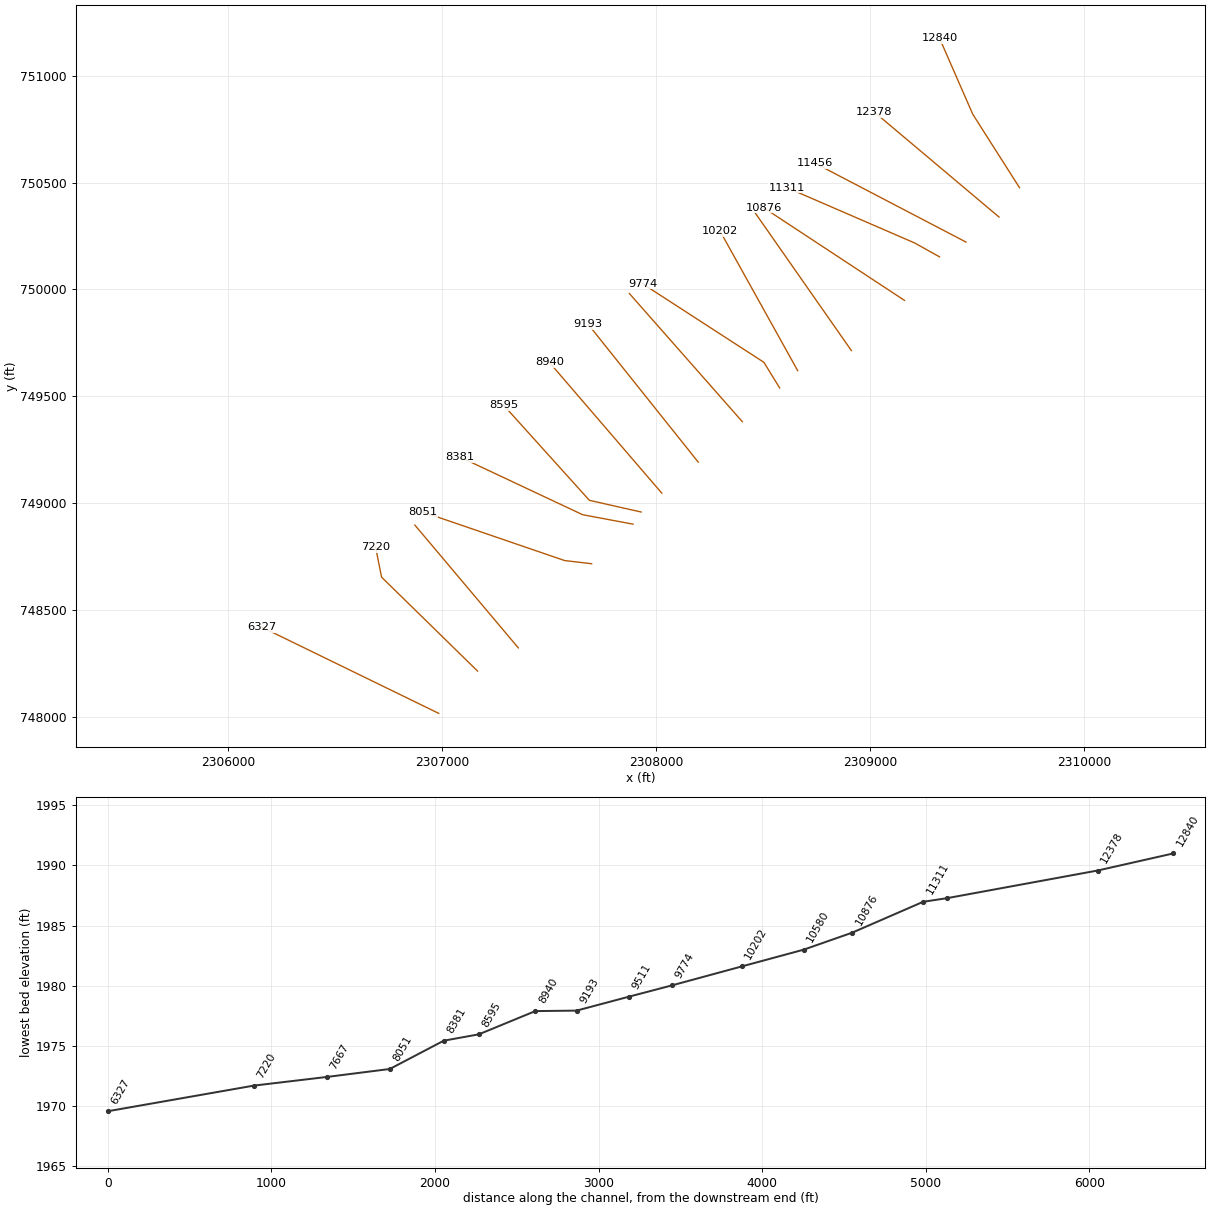
HEC-RAS study CHERRYFK.prj: CHERRYFK

--- CHERRYFK.g01 (geometry) --- (continued)

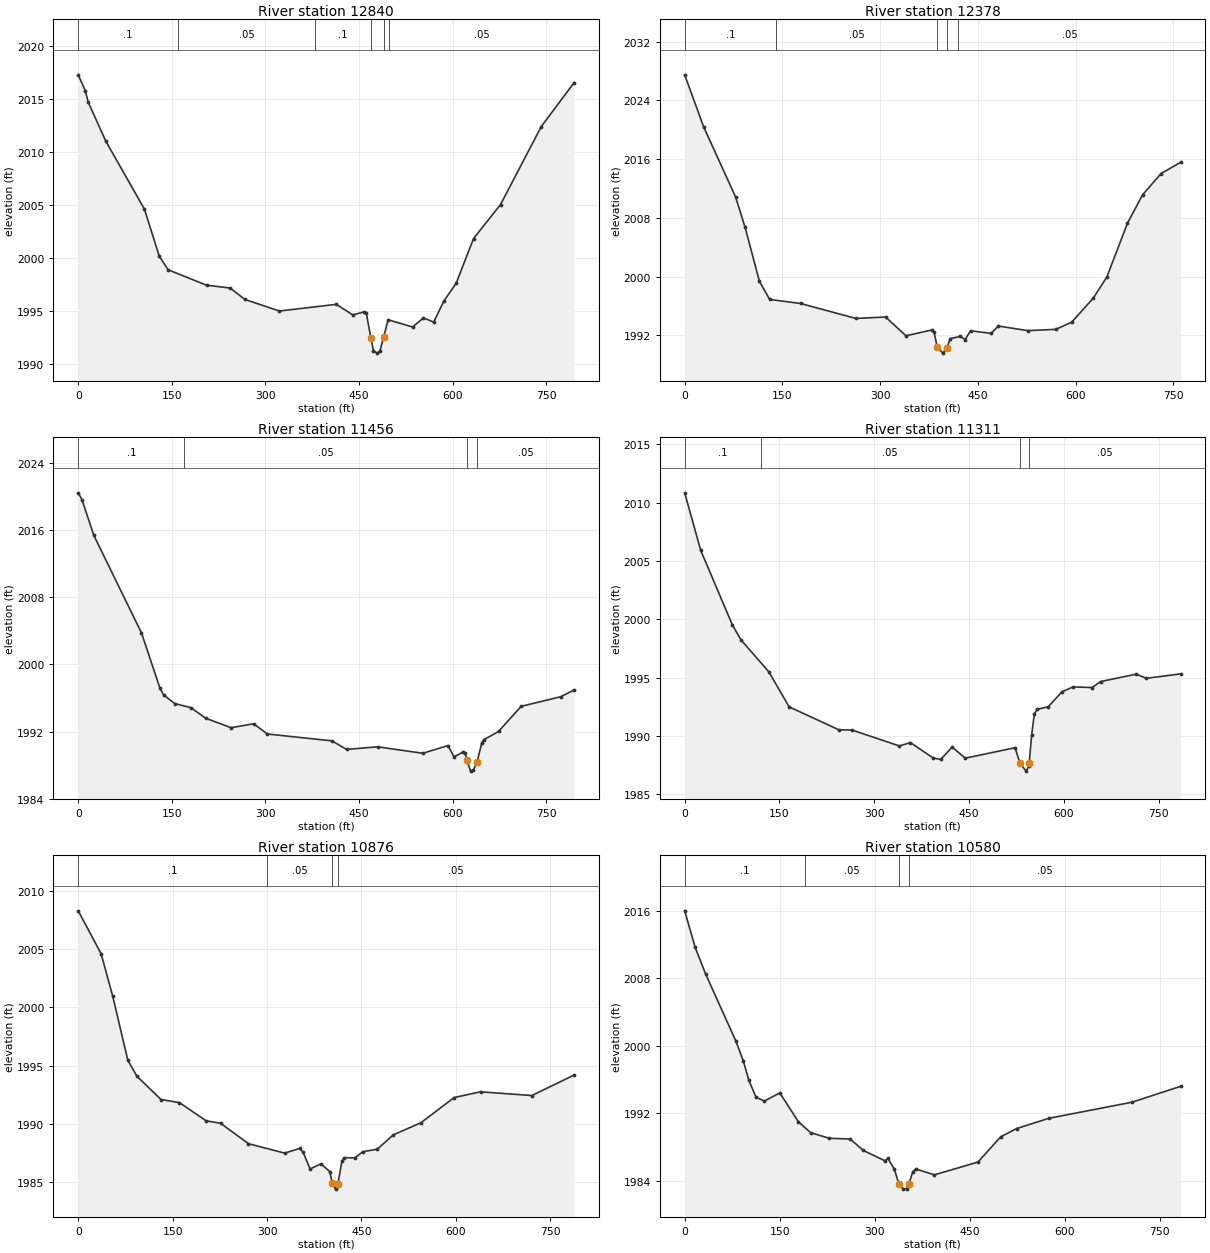
Type RM Length L Ch R = 1 ,12840   ,462.6,462.6,462.6
XS GIS Cut Line= 3
2309699.74913657750475.6760581842309481.15735363750819.444332207
2309326.08796915751174.422441252
#Sta/Elev= 30
       0  2017.3    11.3 2015.81      16 2014.72    44.4 2011.01   106.1 2004.61
   129.8 2000.17     144 1998.88   205.6 1997.42   243.5 1997.15   267.2 1996.07
   322.4 1994.98   413.6 1995.61   439.8 1994.62   458.1 1994.89   461.7 1994.77
   468.91992.473   473.2 1991.23   479.1    1991   483.5  1991.2   489.41992.493
   496.6 1994.15   535.9 1993.47   553.3 1994.33   569.7 1993.93   585.6 1995.88
   605.7  1997.6   633.6 2001.83   676.8 2005.04   742.1 2012.41   794.8 2016.57
#Mann= 6, -1 ,  0
       0     0.1       0     160    0.05       0     380     0.1       0
   468.9   0.045       0   489.4     0.1       0  497.38    0.05       0
Bank Sta=468.9,489.4
XS Rating Curve= 0 ,0
Exp/Cntr(USF)=0,0
Exp/Cntr=0.3,0.1

Type RM Length L Ch R = 1 ,12378   ,921.7,921.7,921.7
XS GIS Cut Line= 2
 2309604.0006858750338.5436564232309021.71364313750828.955984472
#Sta/Elev= 30
       0 2027.47    28.9 2020.43    78.2 2010.83    92.6 2006.74   114.8 1999.34
   130.5 1996.89   177.8 1996.34   262.9  1994.3   308.4  1994.5   339.6 1991.94
   379.3 1992.73   382.9 1992.42   387.8 1990.36   396.3 1989.58   402.5 1990.33
   407.7 1991.56   423.4 1991.86   430.4 1991.43   438.9 1992.62   470.4 1992.27
   481.5 1993.27   526.9 1992.64   569.8 1992.82     594 1993.79   627.3 1997.07
   648.2 1999.97   679.6 2007.25   702.9 2011.13   731.3 2014.03   761.3 2015.56
#Mann= 5, -1 ,  0
       0     0.1       0     140    0.05       0   387.8   0.045       0
   402.5     0.1       0     420    0.05       0
Bank Sta=387.8,402.5
XS Rating Curve= 0 ,0
Exp/Cntr(USF)=0,0
Exp/Cntr=0.3,0.1

Type RM Length L Ch R = 1 ,11456   ,145.4,145.4,145.4
XS GIS Cut Line= 2
 2309449.3961544 750221.586464342308745.04485382750589.642714245
#Sta/Elev= 30
       0 2020.47     5.9 2019.67      25  2015.4   101.4 2003.76     131 1997.17
     137 1996.36   154.7 1995.34   180.5 1994.85   204.5 1993.58   245.1 1992.46
   281.2 1992.93     303 1991.71   406.7 1990.89   430.1 1989.87   479.8 1990.18
   552.1 1989.41   592.6 1990.33   602.3 1988.97   617.2 1989.59   619.7 1989.47
   622.7 1988.63   628.7 1987.28   633.2 1987.38   639.21988.392   646.8 1990.69
   649.8 1991.02   673.5 1992.01   709.9 1995.01   773.1 1996.15   794.7 1996.96
#Mann= 4, -1 ,  0
       0     0.1       0     170    0.05       0   622.7   0.045       0
   639.2    0.05       0
Bank Sta=622.7,639.2
XS Rating Curve= 0 ,0
Exp/Cntr(USF)=0,0
Exp/Cntr=0.3,0.1

Type RM Length L Ch R = 1 ,11311   ,434.8,434.8,434.8
XS GIS Cut Line= 3
2309325.89344154750152.3111267832309210.42927317750216.871737058
2308612.00207793750476.355728355
#Sta/Elev= 30
       0 2010.85    25.4 2005.91    75.3 1999.54      89 1998.24   133.1  1995.5
   165.3 1992.49   243.7 1990.53     265  1990.5   339.7 1989.14   357.1 1989.43
   392.7 1988.12   405.1 1987.98   423.1 1989.05   443.9 1988.09   522.8 1988.99
  530.411987.648   540.2 1986.98   544.6 1987.41  545.061987.692   548.9 1990.07
   553.3  1991.9   557.7 1992.28   575.1  1992.5   596.9 1993.78   614.3  1994.2
   644.8 1994.15   657.9 1994.66   714.6  1995.3   730.3 1994.94   784.6 1995.32
#Mann= 4, -1 ,  0
       0     0.1       0     120    0.05       0  530.41   0.045       0
  545.06    0.05       0
Bank Sta=530.41,545.06
XS Rating Curve= 0 ,0
Exp/Cntr(USF)=0,0
Exp/Cntr=0.3,0.1

Type RM Length L Ch R = 1 ,10876   ,296.2,296.2,296.2
XS GIS Cut Line= 2
2309162.00881546749948.6968943782308503.98721073750381.997913338
#Sta/Elev= 30
       0 2008.29    36.3 2004.62    54.9 2000.95    78.8 1995.47    93.2  1994.1
   131.5  1992.1   160.9 1991.83   203.3 1990.27   226.3 1990.06   270.4 1988.31
   327.9  1987.5   351.8  1987.9   357.3 1987.58   368.4 1986.14   385.7 1986.58
   399.7 1985.91  403.771984.906   408.8 1984.41   412.71984.886   418.9  1986.8
   422.7 1987.11   439.5 1987.09   452.2 1987.62   475.3 1987.84   500.3 1989.06
   544.6 1990.11   597.3 1992.27   639.2 1992.76   720.7 1992.44   787.9  1994.2
#Mann= 4, -1 ,  0
       0     0.1       0     300    0.05       0  403.77   0.045       0
   412.7    0.05       0
Bank Sta=403.77,412.7
XS Rating Curve= 0 ,0
Exp/Cntr(USF)=0,0
Exp/Cntr=0.3,0.1

Type RM Length L Ch R = 1 ,10580   ,377.8,377.8,377.8
XS GIS Cut Line= 2
2308913.69877594749714.0439070322308465.49915461750355.925359189
#Sta/Elev= 30
       0    2016    16.6 2011.66    33.1  2008.5    80.9 2000.54    92.4 1998.24
   101.4 1995.89   112.5 1993.91   125.8 1993.44   150.2 1994.41   179.5 1990.99
   198.7  1989.7   228.2 1989.03   261.2 1988.94     282 1987.59   316.1 1986.36
   320.9 1986.64     331 1985.37     338 1983.64     345    1983   350.2 1983.03
  353.95 1983.59     360 1985.05   364.8  1985.4   394.1 1984.69     463 1986.21
   498.7 1989.19   523.9 1990.18     575  1991.4   706.3 1993.31   782.9 1995.19
#Mann= 4, -1 ,  0
       0     0.1       0     190    0.05       0     338   0.045       0
  353.95    0.05       0
Bank Sta=338,353.95
XS Rating Curve= 0 ,0
Exp/Cntr(USF)=0,0
Exp/Cntr=0.3,0.1

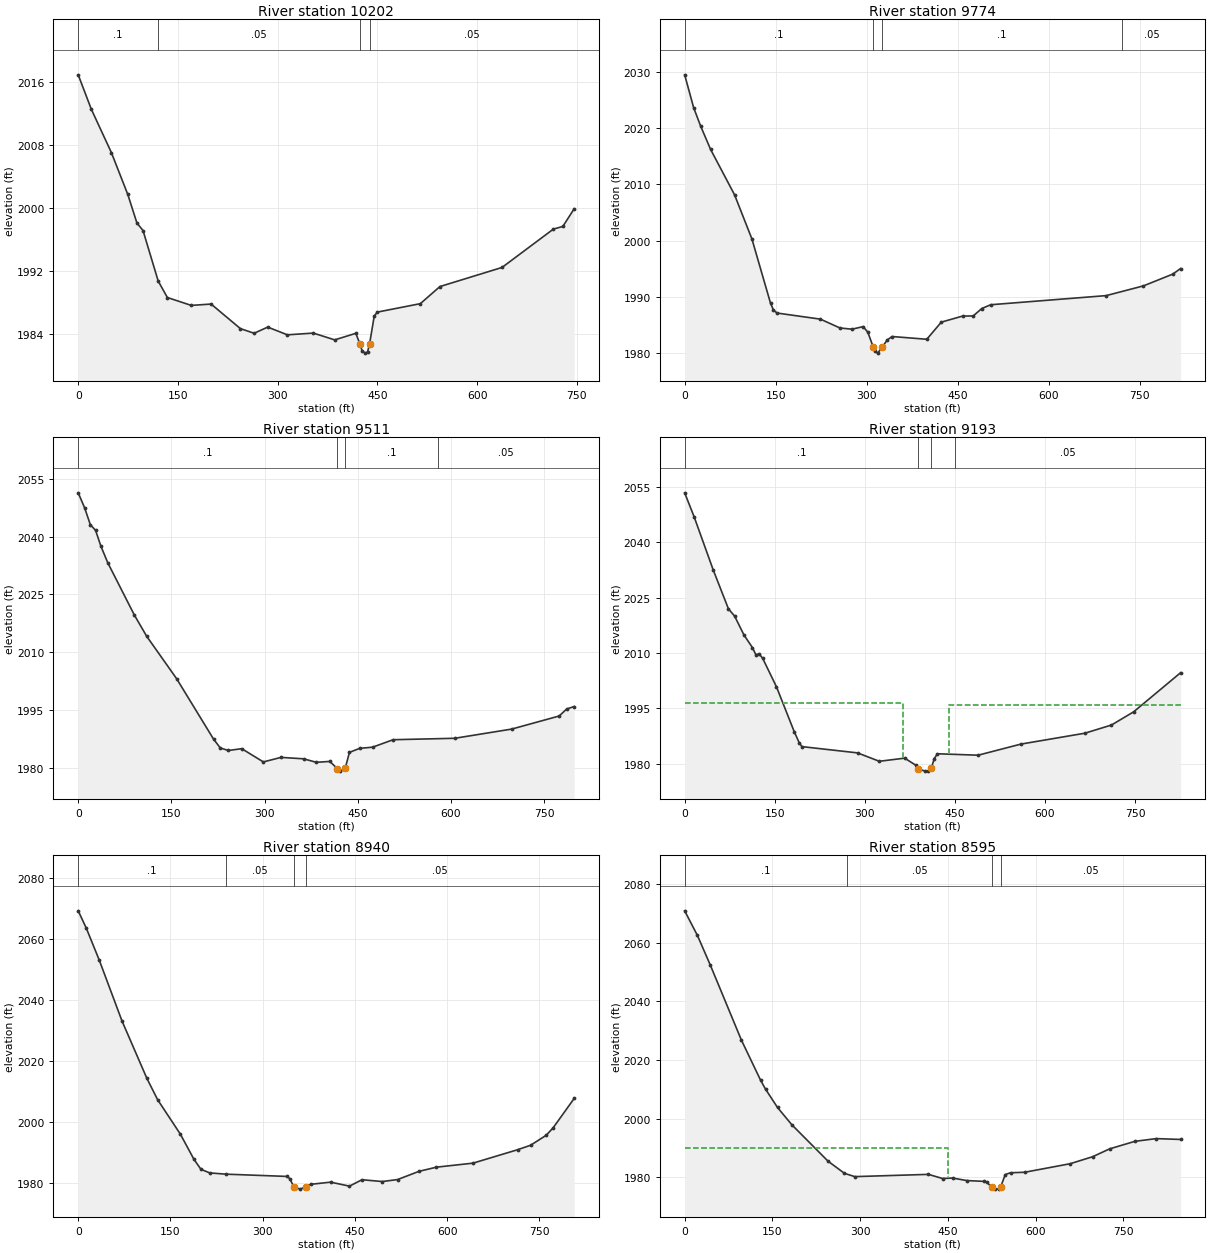
Type RM Length L Ch R = 1 ,10202   ,428,428,428
XS GIS Cut Line= 2
2308662.83939699  749619.99198482308300.38806459750272.030721941
#Sta/Elev= 30
       0 2016.89    19.7 2012.53    49.9 2007.03    74.6 2001.72    88.3 1998.11
    97.5 1997.15   120.3 1990.75   134.1 1988.66   170.1 1987.66   199.9 1987.83
   243.9 1984.72   264.6 1984.13   285.1 1984.91   314.6 1983.93   353.7 1984.15
   385.8 1983.29   417.6 1984.12   423.5 1982.82     427 1981.92   431.5 1981.61
   435.2 1981.76   438.2 1982.75   445.3 1986.31   449.9 1986.81   514.6 1987.88
   544.1 1990.05   637.5 1992.47   714.7 1997.33     729 1997.67     746 1999.91
#Mann= 4, -1 ,  0
       0     0.1       0     120    0.05       0   423.5   0.045       0
   438.2    0.05       0
Bank Sta=423.5,438.2
XS Rating Curve= 0 ,0
Exp/Cntr(USF)=0,0
Exp/Cntr=0.3,0.1

Type RM Length L Ch R = 1 ,9774    ,263.3,263.3,263.3
XS GIS Cut Line= 3
 2308578.5256357749539.1525276152308504.93547005 749658.99936882
2307937.23990645750026.950197079
#Sta/Elev= 30
       0 2029.43    14.8 2023.59    26.4  2020.3    42.7 2016.19    82.2 2008.13
   110.8 2000.29   141.5 1988.87   146.3 1987.68     152 1987.15   223.7 1986.06
   255.9 1984.49   275.8 1984.28   294.1 1984.74   301.8 1983.72   310.5 1981.16
   313.1 1980.41   317.9 1980.03   325.5 1981.09   333.6 1982.36   341.7 1982.98
   398.9 1982.49   422.8 1985.53     458 1986.61   475.4 1986.63   489.5 1987.95
   504.3 1988.62   694.5 1990.24   755.9 1991.97   804.1 1994.05   817.1 1995.05
#Mann= 4, -1 ,  0
       0     0.1       0   310.5   0.045       0   325.5     0.1       0
  720.64    0.05       0
Bank Sta=310.5,325.5
XS Rating Curve= 0 ,0
Exp/Cntr(USF)=0,0
Exp/Cntr=0.3,0.1

Type RM Length L Ch R = 1 ,9511    ,317.8,317.8,317.8
XS GIS Cut Line= 2
 2308404.0118143749381.4593155042307876.26519777749980.693521527
#Sta/Elev= 30
       0 2051.38    10.3 2047.49    19.5 2043.12      28 2041.62    36.5 2037.53
    47.6 2033.21    90.5  2019.6   110.2 2014.13   158.4 2003.11   217.9 1987.41
   228.8  1985.1   241.8 1984.45   263.3 1984.92   298.1 1981.48   326.6 1982.66
   362.9 1982.29   383.4 1981.38     405 1981.61   417.4 1979.73     422 1979.09
  429.891979.845   436.7 1983.96   453.1    1985     474 1985.31     507 1987.25
   606.2 1987.62   697.9 1990.01   774.4 1993.41   786.5 1995.23   798.5 1995.87
#Mann= 4, -1 ,  0
       0     0.1       0   417.4   0.045       0  429.89     0.1       0
     580    0.05       0
Bank Sta=417.4,429.89
XS Rating Curve= 0 ,0
Exp/Cntr(USF)=0,0
Exp/Cntr=0.3,0.1

Type RM Length L Ch R = 1 ,9193    ,252.5,252.5,252.5
XS GIS Cut Line= 2
2308197.95935047749192.2274609712307682.82819091749837.718342546
#Sta/Elev= 30
       0 2053.44    15.7 2046.95    47.5 2032.53    72.9 2021.95    83.1 2020.02
    98.7 2014.88   112.9 2011.43   118.6 2009.49     124 2009.76     130  2008.5
   152.8 2000.83   182.4 1988.65   190.6 1985.68   195.2 1984.59   287.8 1982.89
   324.1 1980.61   366.3 1981.46     385 1979.53   388.71978.609   400.2 1977.94
   405.5 1977.95   410.6 1978.76   415.7 1981.36   420.9 1982.65   488.6 1982.26
   559.8 1985.27   666.5 1988.23   710.7 1990.45   747.7 1994.04   825.8 2004.65
#Mann= 4, -1 ,  0
       0     0.1       0   388.7   0.045       0   410.6     0.1       0
     450    0.05       0
#XS Ineff= 2 , 0
           363.9 1996.55     440            1996
Permanent Ineff=
       F       F
Bank Sta=388.7,410.6
XS Rating Curve= 0 ,0
Exp/Cntr(USF)=0,0
Exp/Cntr=0.3,0.1

Type RM Length L Ch R = 1 ,8940    ,344.8,344.8,344.8
XS GIS Cut Line= 2
2308027.65068139749047.1497058282307502.00664102 749658.99936882
#Sta/Elev= 30
       0 2069.16    13.2 2063.45    34.3 2052.96    71.2 2033.05   111.7 2014.21
   129.2 2007.21   166.2 1995.91   188.3 1987.65   199.6 1984.41   213.8 1983.22
     240 1982.81   340.2 1982.06   344.3 1981.26   350.7 1978.67   361.3  1977.9
   369.8 1978.67   378.3 1979.48   410.5 1980.19   441.2 1978.88   461.5 1980.98
   494.6 1980.39   519.5 1981.04   554.2 1983.73   582.6  1985.1   642.1 1986.42
   714.6 1990.82   735.8 1992.29   761.3 1995.58   772.5 1998.03   806.6 2007.63
#Mann= 4, -1 ,  0
       0     0.1       0     240    0.05       0   350.7   0.045       0
   369.8    0.05       0
Bank Sta=350.7,369.8
XS Rating Curve= 0 ,0
Exp/Cntr(USF)=0,0
Exp/Cntr=0.3,0.1

Type RM Length L Ch R = 1 ,8595    ,214.8,214.8,214.8
XS GIS Cut Line= 3
2307930.93217797748958.8415070462307689.13591939749013.508487244
2307287.54387255749459.254633479
#Sta/Elev= 30
       0 2070.83    21.8 2062.43    43.8 2052.35    97.1 2026.71     130 2013.01
   138.2 2010.06   158.7  2003.8   183.3 1997.89   245.1  1985.5   273.2 1981.35
   290.8 1980.23   416.7    1981   440.9 1979.59   457.9 1979.75   482.4 1978.89
   512.3 1978.61   516.7 1978.31  524.931976.601   530.2 1975.97   537.2 1976.04
   540.1 1976.65   548.1 1980.94   557.1 1981.55   581.3 1981.72     659 1984.63
   697.5 1987.02   726.6  1989.7   769.7 1992.26   806.3 1993.19   847.9  1992.9
#Mann= 4, -1 ,  0
       0     0.1       0   277.9    0.05       0  524.93   0.045       0
   540.1    0.05       0
#XS Ineff= 2 , 0
             450    1990
Permanent Ineff=
       F       F
Bank Sta=524.93,540.1
XS Rating Curve= 0 ,0
Exp/Cntr(USF)=0,0
Exp/Cntr=0.3,0.1

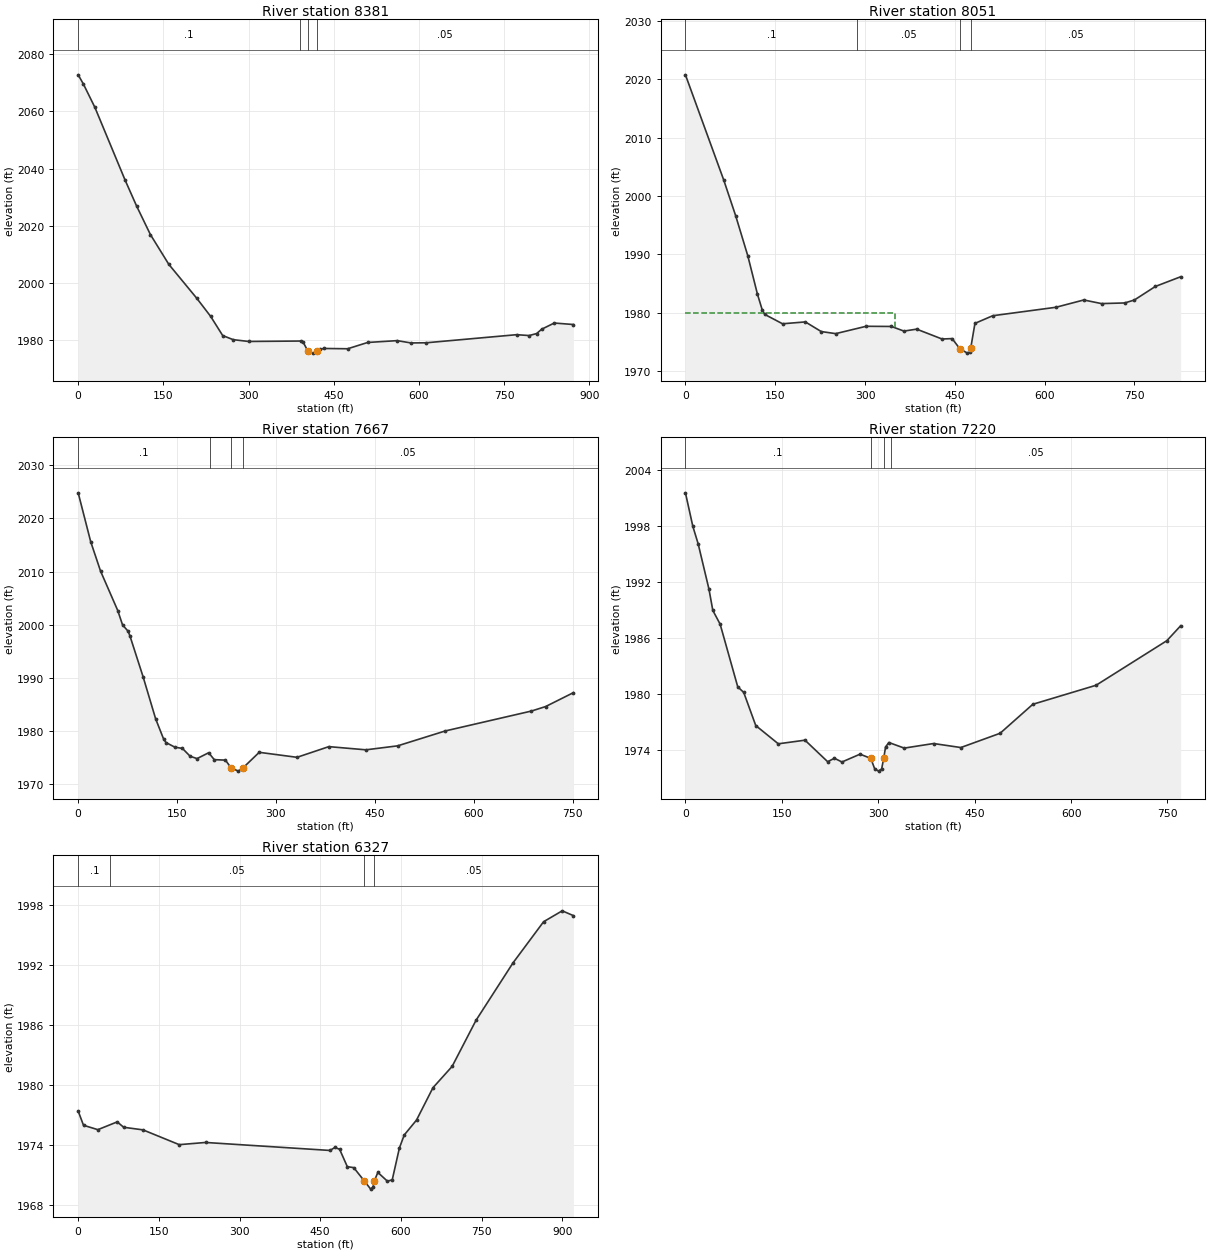
Type RM Length L Ch R = 1 ,8381    ,329.8,329.8,329.8
XS GIS Cut Line= 3
2307893.08580706748902.0719506862307657.59727697748946.226050077
2307085.69656105749215.355798747
#Sta/Elev= 30
       0  2072.8     9.1 2069.61    29.4 2061.42    82.3 2036.11   102.8 2026.92
   127.1 2016.93   159.6 2006.48   208.5 1994.69   233.1 1988.32   254.4 1981.58
   272.9 1980.15     300 1979.52   391.5 1979.67   395.9 1979.31  404.481976.098
   413.6 1975.44   420.2 1976.07     425 1976.79   432.3 1977.07   474.4 1976.97
   509.6 1979.17   561.5 1979.81     586    1979   612.6 1979.06   771.7 1981.89
   793.8 1981.59     807 1982.29   815.9 1983.81     838 1985.97   871.7 1985.45
#Mann= 4, -1 ,  0
       0     0.1       0  389.59    0.05       0  404.48   0.045       0
   420.2    0.05       0
Bank Sta=404.48,420.2
XS Rating Curve= 0 ,0
Exp/Cntr(USF)=0,0
Exp/Cntr=0.3,0.1

Type RM Length L Ch R = 1 ,8051    ,383.5,383.5,383.5
XS GIS Cut Line= 3
 2307699.6488002748717.0452484752307573.49423051748731.763281606
2306911.18273965748958.841507046
#Sta/Elev= 30
       0 2020.79    63.9 2002.78      84 1996.61   104.2 1989.76   120.3 1983.19
   128.4 1980.46   132.6 1979.72   162.2 1978.12   200.3 1978.44   226.8 1976.79
     251 1976.43   301.8 1977.69   344.1 1977.66   364.9 1976.87   386.3  1977.2
   428.6 1975.51   445.5 1975.58   458.2 1973.86   470.9 1973.09   475.1 1973.29
   476.7 1974.04   483.6 1978.19   513.3  1979.5   618.9 1980.95   665.4  1982.2
     695 1981.58   733.8 1981.69     750  1982.2     785 1984.52   827.2 1986.18
#Mann= 4, -1 ,  0
       0     0.1       0  287.01    0.05       0   458.2   0.045       0
   476.7    0.05       0
#XS Ineff= 2 , 0
             350    1980
Permanent Ineff=
       F       F
Bank Sta=458.2,476.7
XS Rating Curve= 0 ,0
Exp/Cntr(USF)=0,0
Exp/Cntr=0.3,0.1

Type RM Length L Ch R = 1 ,7667    ,447,447,447
XS GIS Cut Line= 2
2307357.04824913748323.2636412992306873.33636874748897.866798363
#Sta/Elev= 30
       0 2024.81      19 2015.61    33.9 2010.09      60 2002.66    67.3 1999.95
    75.8 1998.75    78.6 1997.84    98.5 1990.17   117.5 1982.27   129.7 1978.43
   133.2 1977.81   146.8 1976.93   158.1 1976.71   169.8 1975.23   180.3 1974.79
   197.9 1975.89   206.4 1974.59   223.4  1974.5   231.9 1973.04     243 1972.43
   249.8 1973.02   274.6 1975.97   331.9 1975.03   380.2 1977.04   436.5 1976.44
   484.6 1977.19   556.7 1979.99   687.5 1983.74   708.9 1984.58   751.1  1987.2
#Mann= 4, -1 ,  0
       0     0.1       0     200    0.05       0   231.9   0.045       0
   249.8    0.05       0
Bank Sta=231.9,249.8
XS Rating Curve= 0 ,0
Exp/Cntr(USF)=0,0
Exp/Cntr=0.3,0.1

Type RM Length L Ch R = 1 ,7220    ,893.1,893.1,893.1
XS GIS Cut Line= 3
2307166.32642148748215.0259953142306717.93302058748654.077867029
2306689.90843303 748794.20080481
#Sta/Elev= 30
       0 2001.56    11.5 1997.97    19.8 1996.09    36.6 1991.23    42.6 1988.95
      54 1987.47    81.4 1980.75    90.7 1980.15   109.4  1976.6   144.5 1974.64
     186 1975.03   221.3 1972.72   231.8 1973.09   243.5 1972.69   271.7 1973.53
   288.41973.076   294.4 1971.97   300.4 1971.71   305.3 1971.95   308.5  1973.1
   311.4  1974.3   316.5 1974.78   340.4 1974.18   386.1 1974.67   428.5 1974.24
   489.6 1975.77   540.5 1978.88   638.9 1980.92     749  1985.7   770.5  1987.3
#Mann= 4, -1 ,  0
       0     0.1       0   288.4   0.045       0   308.5     0.1       0
     320    0.05       0
Bank Sta=288.4,308.5
XS Rating Curve= 0 ,0
Exp/Cntr(USF)=0,0
Exp/Cntr=0.3,0.1

Type RM Length L Ch R = 1 ,6327    ,217.9,217.9,217.9
XS GIS Cut Line= 2
2306985.10075529748016.9855765842306157.44126946748420.539637393
#Sta/Elev= 30
       0 1977.39     9.9 1975.97    36.6 1975.53    72.6 1976.31    84.6 1975.77
   120.5 1975.51   187.9 1974.03   236.9 1974.25   468.3 1973.45   477.2 1973.75
   486.1 1973.57   500.4 1971.83   512.4 1971.73   531.4 1970.44   543.9 1969.58
   548.3 1969.78   550.81970.421   557.2 1971.25   575.1 1970.37     584 1970.52
   597.3  1973.7   606.3    1975   629.1 1976.49   659.7 1979.73   695.3 1981.86
   739.7 1986.47   808.5 1992.22   865.4 1996.34     900 1997.43   920.8 1996.95
#Mann= 4, -1 ,  0
       0     0.1       0      60    0.05       0   531.4   0.045       0
   550.8    0.05       0
Bank Sta=531.4,550.8
XS Rating Curve= 0 ,0
Exp/Cntr(USF)=0,0
Exp/Cntr=0.3,0.1