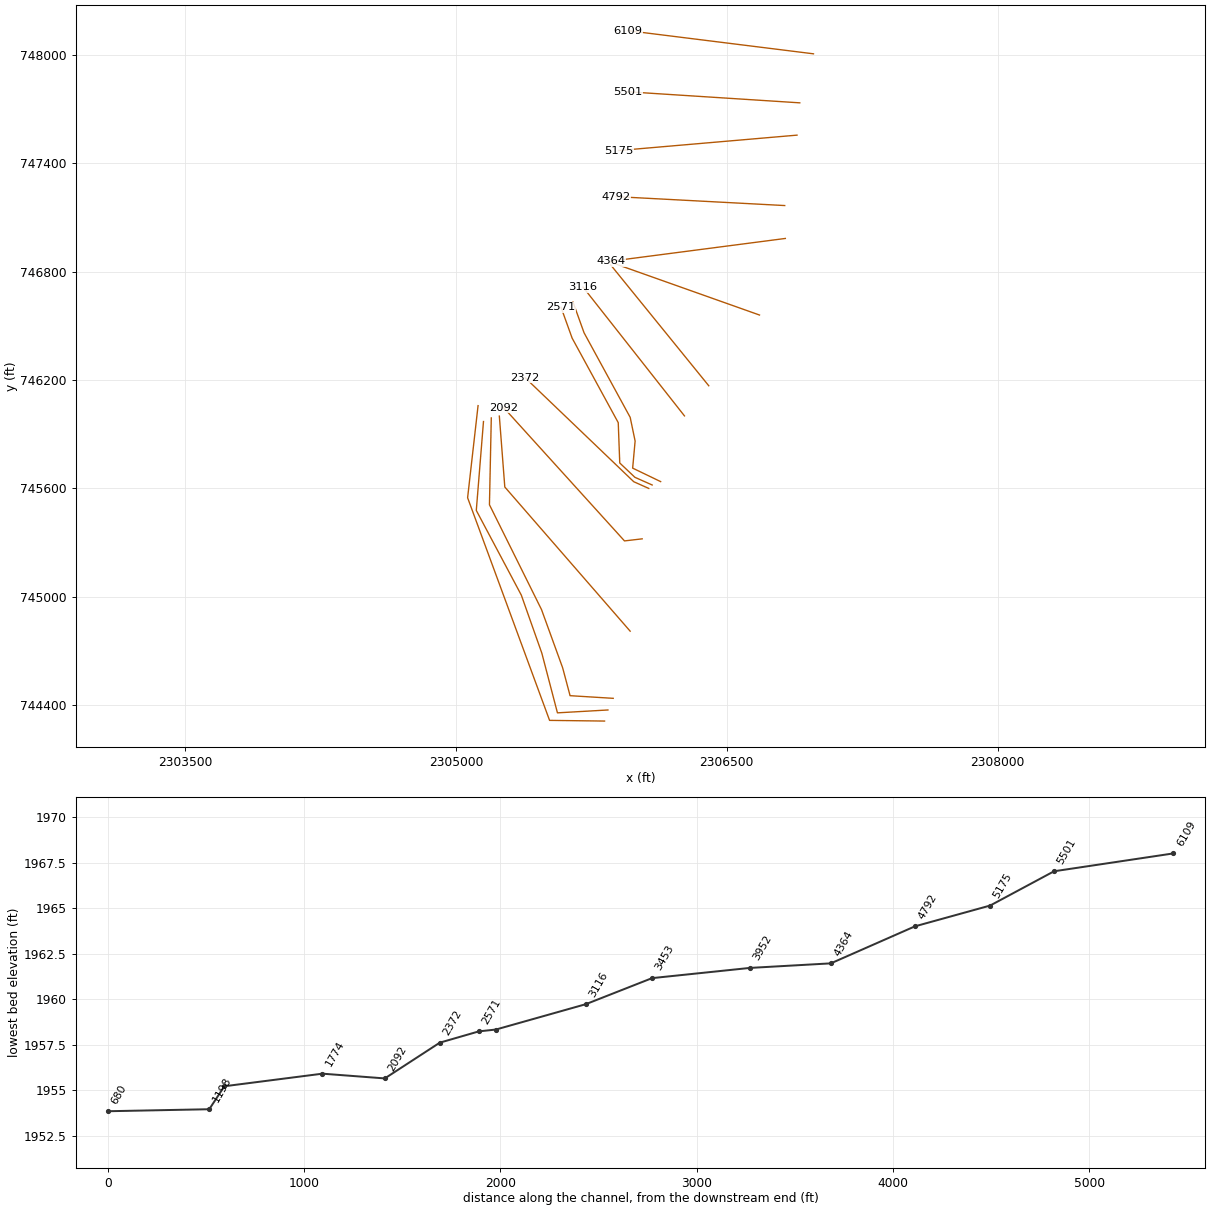
HEC-RAS study CHERRYFK.prj: CHERRYFK

--- CHERRYFK.g01 (geometry) --- (continued)

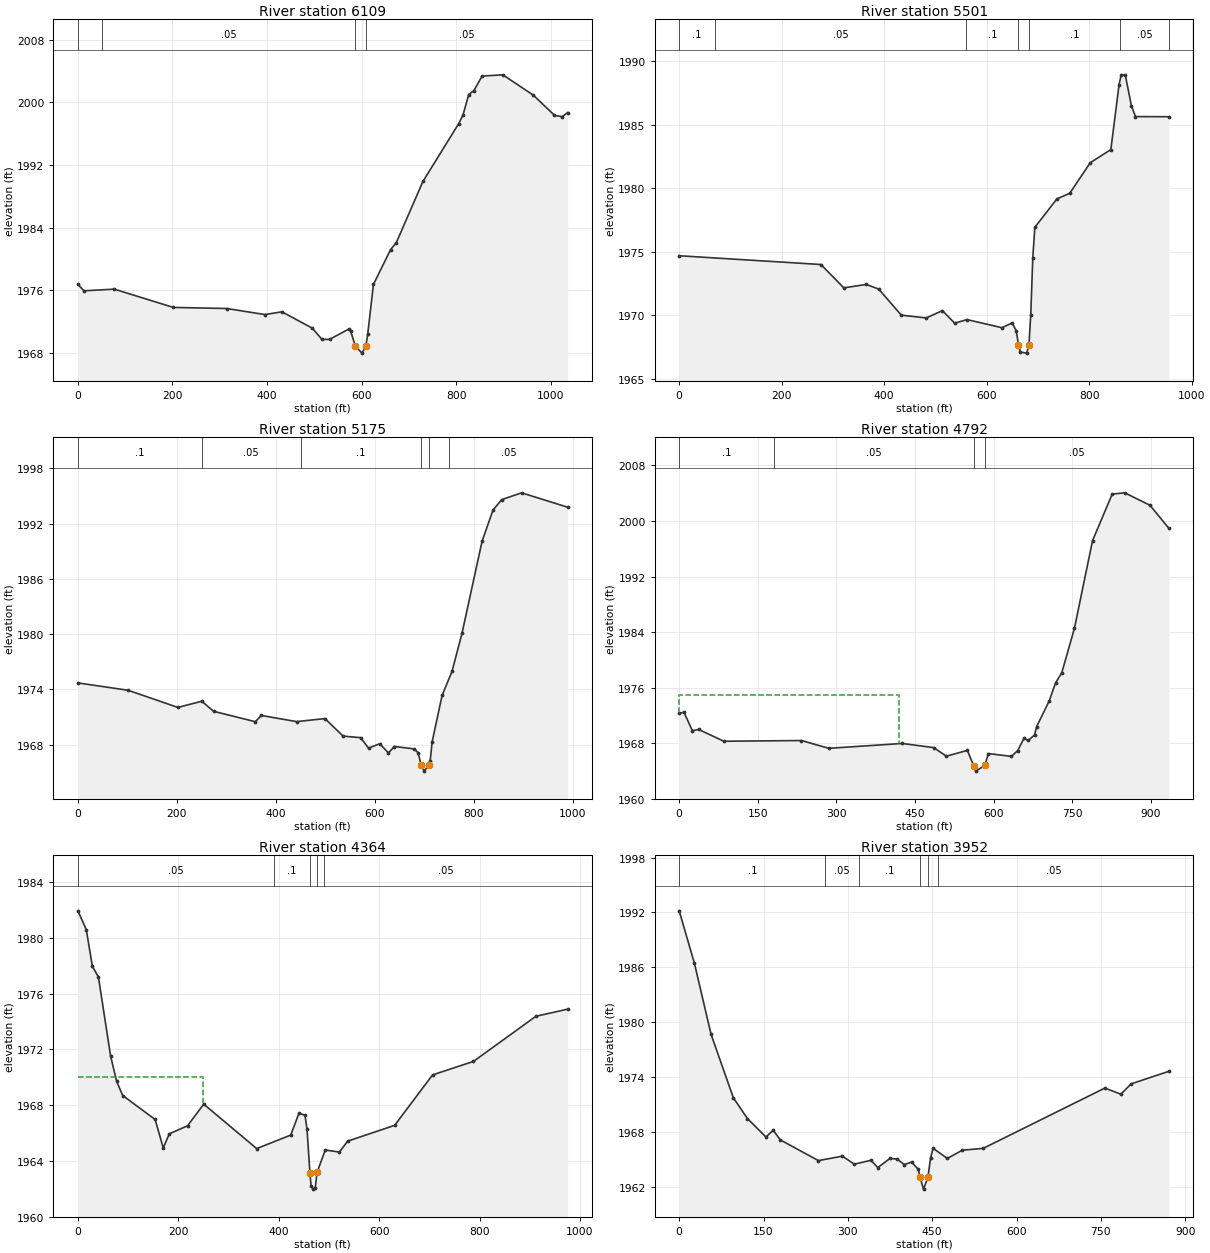
Type RM Length L Ch R = 1 ,6109    ,608.2,608.2,608.2
XS GIS Cut Line= 2
2306980.56775298748006.3745058942305952.40801001748134.631651744
#Sta/Elev= 30
       0 1976.78    12.5 1975.95      77 1976.16   201.9 1973.83     315 1973.69
   395.4 1972.92   431.7 1973.27   496.2 1971.17   516.4 1969.74   532.5 1969.76
   572.8 1971.06   576.8 1970.84     587 1968.89     601    1968   609.1 1968.87
   613.1 1970.42   625.2 1976.77   661.5 1981.21   673.6  1982.1     730 1989.91
   805.7 1997.29   814.7 1998.38   826.8 2000.99   837.9  2001.5     855 2003.34
   898.8  2003.5   963.4 2000.91  1008.1 1998.34  1024.4 1998.16  1036.1 1998.68
#Mann= 4, -1 ,  0
       0     0.1       0      50    0.05       0     587   0.045       0
   609.1    0.05       0
Bank Sta=587,609.1
XS Rating Curve= 0 ,0
Exp/Cntr(USF)=0,0
Exp/Cntr=0.3,0.1

Type RM Length L Ch R = 1 ,5501    ,325.6,325.6,325.6
XS GIS Cut Line= 2
2306904.74885659  747734.84782042305951.02030974747796.158941269
#Sta/Elev= 30
       0 1974.69   276.6    1974   321.2 1972.16   365.3 1972.43   389.4 1972.06
   433.5 1970.01   482.2 1969.79   513.6 1970.37   537.5 1969.38   561.7 1969.66
   629.9 1969.02   649.9  1969.4   657.9 1968.76   662.1 1967.65   665.9  1967.1
     678 1967.02  682.47 1967.66     686 1970.01     690 1974.53     694 1976.93
   737.1 1979.17   762.1 1979.61   802.2 1982.02   842.3 1983.05   858.3 1988.15
   862.4 1988.92   870.4 1988.94   882.4 1986.51   890.4 1985.65   955.7 1985.64
#Mann= 7, -1 ,  0
       0     0.1       0      70    0.05       0     560     0.1       0
   662.1   0.045       0  682.47     0.1       0     860    0.05       0
   955.7    0.08       0
Bank Sta=662.1,682.47
XS Rating Curve= 0 ,0
Exp/Cntr(USF)=0,0
Exp/Cntr=0.3,0.1

Type RM Length L Ch R = 1 ,5175    ,383,383,383
XS GIS Cut Line= 2
2306889.42107638747556.023717866 2305903.3338824747470.869383326
#Sta/Elev= 30
       0 1974.71   101.6 1973.91     202 1972.05   250.2 1972.72   274.3 1971.63
   358.6  1970.5   370.6 1971.18   442.1 1970.51   499.2 1970.84     536 1968.94
   571.4 1968.77   587.4 1967.63   609.9 1968.11   627.6 1967.12   639.6 1967.81
   679.8 1967.55   687.8 1967.11  693.421965.815   699.8 1965.14   709.7 1965.83
   711.9 1966.24   715.9 1968.33     736 1973.35     756 1975.95   776.2 1980.08
   816.8 1990.08     839 1993.47   856.4 1994.59   896.6 1995.33   989.8 1993.77
#Mann= 6, -1 ,  0
       0     0.1       0     250    0.05       0     450     0.1       0
  693.42   0.045       0   709.7     0.1       0     750    0.05       0
Bank Sta=693.42,709.7
XS Rating Curve= 0 ,0
Exp/Cntr(USF)=0,0
Exp/Cntr=0.3,0.1

Type RM Length L Ch R = 1 ,4792    ,428.4,428.4,428.4
XS GIS Cut Line= 2
2306821.29760874747166.0168656722305888.00610218747215.406379705
#Sta/Elev= 30
       0 1972.31     9.1 1972.47    25.2 1969.82    37.2 1969.99    85.2  1968.3
   233.4  1968.4   285.5 1967.28   425.7 1967.98   485.8 1967.38   509.8 1966.15
   549.9 1966.98   561.9 1964.79   565.9    1964  583.321964.815   589.9 1966.53
     634 1966.12     646 1966.96     658 1968.73     666 1968.41   678.1  1969.2
   682.1  1970.4   706.1  1974.1   718.1 1976.67   730.1 1978.16   754.2 1984.54
   788.7 1997.14   826.3 2003.86   850.3 2004.04   898.4 2002.25   934.6 1998.92
#Mann= 4, -1 ,  0
       0     0.1       0     180    0.05       0   561.9   0.045       0
  583.32    0.05       0
#XS Ineff= 2 , 0
             420    1975
Permanent Ineff=
       F       F
Bank Sta=561.9,583.32
XS Rating Curve= 0 ,0
Exp/Cntr(USF)=0,0
Exp/Cntr=0.3,0.1

Type RM Length L Ch R = 1 ,4364    ,412,412,412
XS GIS Cut Line= 2
2306824.70378212746983.7865897562305857.35054175746857.758174637
#Sta/Elev= 30
       0 1981.95    16.7  1980.6    28.8 1977.97    40.9 1977.19    65.1 1971.53
    77.2  1969.7    89.3 1968.69   153.8 1966.97     170 1964.93   182.1 1965.94
   218.4 1966.52   250.6 1968.07   356.1 1964.88   423.9 1965.85   440.2 1967.41
   452.3 1967.28   456.4 1966.26  462.131963.134   464.4  1962.2   468.5 1961.97
   472.5 1962.03   476.5 1963.19   492.7 1964.78   520.9 1964.63     537 1965.41
   630.9 1966.55   706.4 1970.17   787.9 1971.14   912.2 1974.38   975.5 1974.89
#Mann= 5, -1 ,  0
       0    0.05       0     390     0.1       0  462.13   0.045       0
   476.5     0.1       0     490    0.05       0
#XS Ineff= 2 , 0
             250    1970
Permanent Ineff=
       F       F
Bank Sta=462.13,476.5
XS Rating Curve= 0 ,0
Exp/Cntr(USF)=0,0
Exp/Cntr=0.3,0.1

Type RM Length L Ch R = 1 ,3952    ,498.6,498.6,498.6
XS GIS Cut Line= 2
 2306681.6445001746559.7180037472305860.75671513746850.945827874
#Sta/Elev= 30
       0 1992.18      27 1986.46    56.7 1978.66    96.3 1971.72   121.3 1969.45
   154.4 1967.42   167.1 1968.17   179.8 1967.11   247.7 1964.84   290.2 1965.33
   311.4 1964.45   341.1 1964.88   353.2 1964.08   375.1 1965.09   387.8    1965
   400.2 1964.41   413.3 1964.68   425.2 1963.89   428.4    1963   434.5 1961.72
  442.331963.026   447.2 1965.17   451.5 1966.19   476.9 1965.08   503.5 1965.98
   540.6 1966.18     757 1972.78   785.5 1972.11   803.7 1973.24     871 1974.62
#Mann= 6, -1 ,  0
       0     0.1       0     260    0.05       0     320     0.1       0
   428.4   0.045       0  442.33     0.1       0     460    0.05       0
Bank Sta=428.4,442.33
XS Rating Curve= 0 ,0
Exp/Cntr(USF)=0,0
Exp/Cntr=0.3,0.1

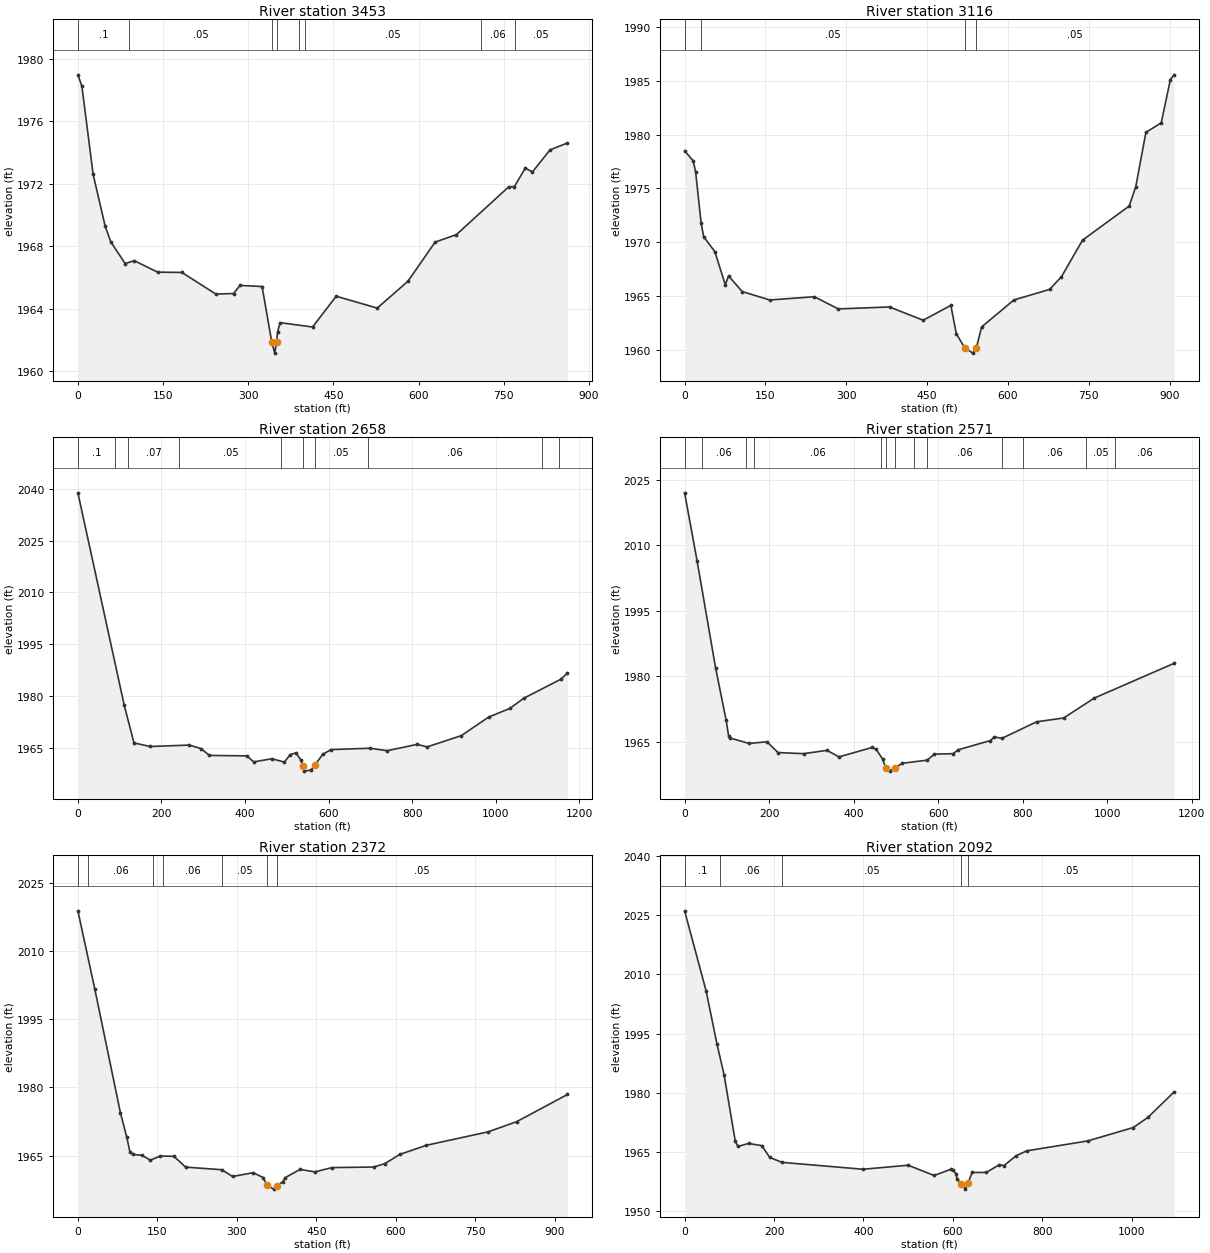
Type RM Length L Ch R = 1 ,3453    ,337.8,337.8,337.8
XS GIS Cut Line= 2
2306400.63519611746168.0080648622305857.35054175746837.321134347
#Sta/Elev= 30
       0 1978.96     7.1 1978.22    26.8  1972.6    47.9  1969.3    57.9 1968.28
    83.2 1966.89    99.4 1967.07   140.4 1966.34   183.2 1966.32   242.9 1964.94
   274.2 1964.97   285.5 1965.49   324.4 1965.42   341.5 1961.85   346.7 1961.16
   349.8 1961.87   351.8 1962.54   356.2 1963.11   413.3 1962.83   454.9  1964.8
   527.2 1964.04   581.3 1965.76   629.1 1968.26   666.6 1968.74   758.8  1971.8
   768.7 1971.81   787.8 1972.99   800.5 1972.75   831.5 1974.16   862.1  1974.6
#Mann= 8, -1 ,  0
       0     0.1       0      90    0.05       0   341.5   0.045       0
   349.8    0.05       0     390     0.1       0     400    0.05       0
     710    0.06       0     770    0.05       0
Bank Sta=341.5,349.8
XS Rating Curve= 0 ,0
Exp/Cntr(USF)=0,0
Exp/Cntr=0.3,0.1

Type RM Length L Ch R = 1 ,3116    ,458,458,458
BEGIN DESCRIPTION:
Structure XS 4
END DESCRIPTION:
XS GIS Cut Line= 2
2306266.09134754746001.1055691642305704.07273958 746714.69889261
#Sta/Elev= 30
       0 1978.49      16 1977.56    20.5 1976.52    30.6  1971.8    35.4 1970.53
    56.1 1969.14    75.5 1966.07    81.6 1966.89   106.8 1965.44   157.9 1964.66
   240.7 1964.96   285.2 1963.83   380.2 1964.01   442.7 1962.78     494 1964.16
   504.2 1961.52   519.4 1960.25   534.7 1959.73  541.161960.175   551.1 1962.16
     611 1964.66   677.3 1965.64   699.3 1966.82   738.4 1970.21   824.9 1973.37
   837.1 1975.16   855.9  1980.2   884.4 1981.09   901.3  1985.1   908.3 1985.54
#Mann= 4, -1 ,  0
       0     0.1       0      30    0.05       0   519.4   0.045       0
  541.16    0.05       0
Bank Sta=519.4,541.16
XS Rating Curve= 0 ,0
Exp/Cntr(USF)=0,0
Exp/Cntr=0.3,0.1

Type RM Length L Ch R = 1 ,2658    ,86.4,86.4,86.4
BEGIN DESCRIPTION:
Structure XS 3
END DESCRIPTION:
XS GIS Cut Line= 6
2306134.20670004745637.1577617722305979.15598488745711.846718152
2305992.78067841745861.7183469422305965.53129135745992.856022134
2305710.06828773746461.2048621042305648.75716686746631.513531185
#Sta/Elev= 30
       0 2038.79   110.8 1977.44   134.2  1966.5   172.9 1965.46   266.6 1965.87
   294.7 1964.85   314.9 1962.88   404.6 1962.75   420.8 1961.01   464.4 1961.92
   494.3 1960.95   508.1 1963.11   521.8  1963.6   533.7 1961.58   537.9 1959.82
   541.9 1958.34   558.3 1958.68   566.5 1959.98     586 1963.17   605.5 1964.56
   699.6 1964.96   740.4 1964.24   812.3 1966.08   835.9 1965.34   917.9 1968.61
   983.3 1973.97  1034.1 1976.46  1067.3 1979.41  1156.6 1984.94  1171.8 1986.71
#Mann= 10, -1 ,  0
       0     0.1       0      90    0.06       0  121.07    0.07       0
  242.86    0.05       0  487.29    0.07       0   537.9   0.045       0
   566.5    0.05       0  693.68    0.06       0 1110.79    0.05       0
 1150.79    0.06       0
Bank Sta=537.9,566.5
XS Rating Curve= 0 ,0
Exp/Cntr(USF)=0,0
Exp/Cntr=0.3,0.1

Type RM Length L Ch R = 1 ,2571    ,199.2,199.2,199.2
BEGIN DESCRIPTION:
Structure XS 2
END DESCRIPTION:
XS GIS Cut Line= 6
2306087.22761849745618.3980487072305991.51905108745660.994244386
  2305907.713288745740.2668346472305899.33079776745963.611902501
2305643.86779414 746431.960742472305582.55667327746602.269411551
#Sta/Elev= 30
       0 2021.99    29.6 2006.38    73.4 1981.84    98.3  1969.9     104 1966.37
   107.3 1965.84   152.5 1964.58     195 1964.96     221  1962.5   281.4 1962.24
   337.1    1963   365.2  1961.5   443.9 1963.66   453.2 1963.24   468.6    1961
     4761958.905   485.5 1958.24     4971958.959   514.9 1960.03     574 1960.76
   591.3 1962.14   635.7 1962.24   646.8 1963.11   723.8 1965.25   732.9 1966.08
     751 1965.75     833 1969.54   896.8 1970.41   969.6 1974.98  1158.4 1982.94
#Mann= 13, -1 ,  0
       0     0.1       0      40    0.06       0  144.76    0.07       0
  164.76    0.06       0  463.86    0.07       0     476   0.045       0
     497    0.07       0  543.86    0.05       0  573.86    0.06       0
  750.26    0.05       0  800.17    0.06       0  950.17    0.05       0
 1017.37    0.06       0
Bank Sta=476,497
XS Rating Curve= 0 ,0
Exp/Cntr(USF)=0,0
Exp/Cntr=0.3,0.1

Type RM Length L Ch R = 1 ,2372    ,280,280,280
BEGIN DESCRIPTION:
Structure XS 1
END DESCRIPTION:
XS GIS Cut Line= 3
 2306068.4385457745599.3416821452305985.08204356745636.645017332
2305383.89244171746212.288318823
#Sta/Elev= 30
       0 2018.82    31.9 2001.61    80.3 1974.39    92.3 1969.01    98.1 1965.86
   103.7 1965.25   120.6 1965.05   136.9 1963.99   155.7 1964.91   181.2 1964.84
   203.3 1962.46   271.4 1961.89   291.9  1960.4   330.7 1961.23   349.8 1960.15
 357.0151958.432   369.7 1957.62 375.225 1958.31   386.1  1959.2   391.6 1960.17
   419.3 1961.96     447 1961.41   479.6 1962.36   557.8 1962.48   578.9 1963.21
   607.6 1965.26   657.5 1967.26   774.2 1970.22   827.9 1972.45   923.7 1978.43
#Mann= 7, -1 ,  0
       0     0.1       0      20    0.06       0  141.32    0.05       0
  161.32    0.06       0  271.32    0.05       0 357.015   0.045       0
 375.225    0.05       0
Bank Sta=357.015,375.225
XS Rating Curve= 0 ,0
Exp/Cntr(USF)=0,0
Exp/Cntr=0.3,0.1

Type RM Length L Ch R = 1 ,2092    ,317.6,317.6,317.6
XS GIS Cut Line= 3
2306031.91574755745320.1829915332305933.94493294745308.721897116
2305264.67637335746047.088909816
#Sta/Elev= 30
       0 2026.08    48.1 2005.82    72.2 1992.47    88.3 1984.61   113.2 1967.89
   119.1 1966.45     143 1967.22   172.7 1966.66   190.6 1963.67     218 1962.43
   399.1 1960.69   500.3 1961.71   558.1 1959.11   595.8 1960.68   601.5 1960.49
   606.7 1959.56   609.9 1958.22619.17971956.868   628.3 1955.66633.65951957.135
   643.3 1959.88   675.1 1959.88   703.9 1961.83   714.7 1961.62   741.7 1964.12
   765.7 1965.35   901.6 1967.85  1003.6 1971.24  1036.4 1973.79  1095.2 1980.27
#Mann= 5, -1 ,  0
       0     0.1       0      80    0.06       0  218.64    0.05       0
619.1797   0.045       0633.6595    0.05       0
Bank Sta=619.1797,633.6595
XS Rating Curve= 0 ,0
Exp/Cntr(USF)=0,0
Exp/Cntr=0.3,0.1

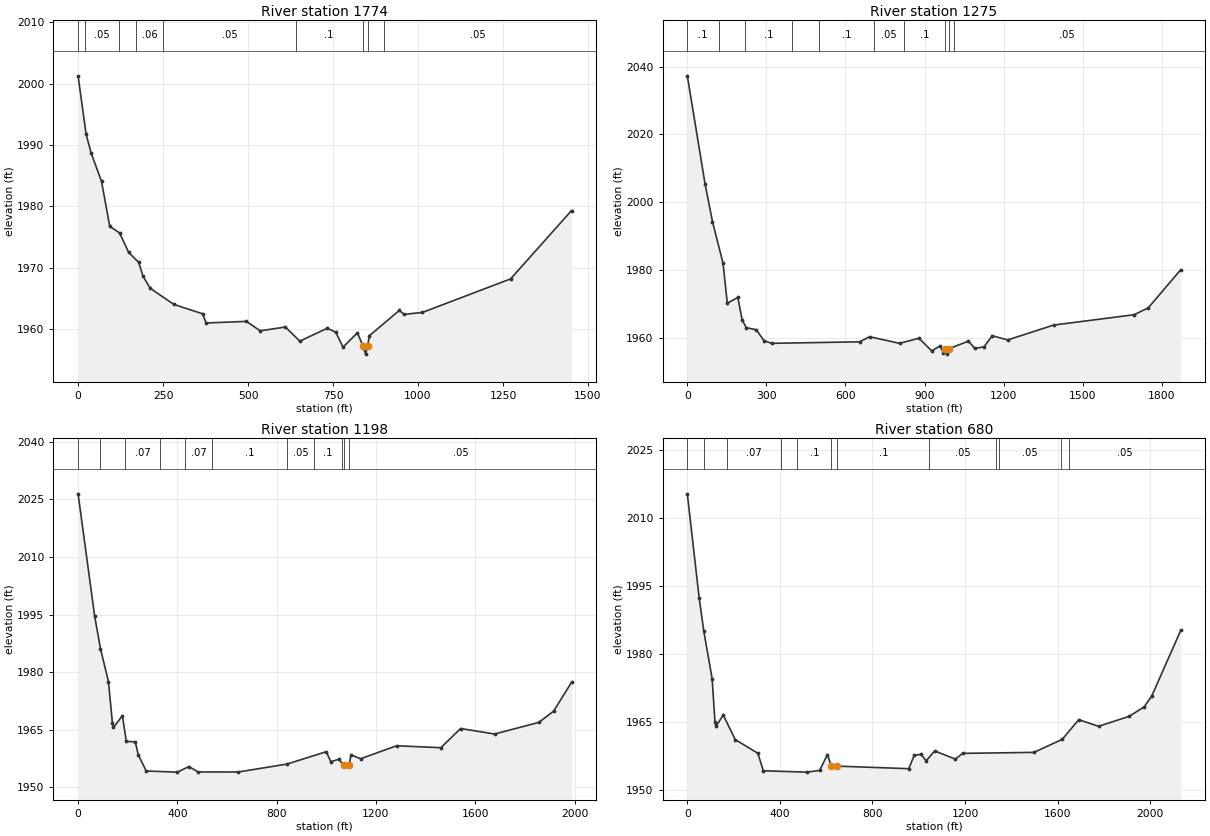
Type RM Length L Ch R = 1 ,1774    ,499.6,499.6,499.6
BEGIN DESCRIPTION:
Structure XS 4
END DESCRIPTION:
XS GIS Cut Line= 3
2305965.26684065744808.9349694982305271.05539215745607.277337192
2305240.83828425745999.853560327
#Sta/Elev= 30
       0  2001.3    23.6 1991.79    38.2 1988.73      69 1984.08    93.1 1976.75
   122.2 1975.68   148.7 1972.51   178.4 1970.88   190.9 1968.64   212.4 1966.65
   281.6 1964.03   366.1  1962.5   376.7    1961   495.4 1961.26   535.7 1959.72
   609.9 1960.34   652.3 1958.04   733.2 1960.14   758.3 1959.48   779.5 1957.06
   821.9  1959.4   837.8 1957.27   845.9 1955.92   851.5 1957.23   857.2 1958.93
   945.1 1963.05   959.3  1962.4  1013.1 1962.72  1272.5 1968.19  1451.7 1979.33
#Mann= 9, -1 ,  0
       0     0.1       0      20    0.05       0     120    0.07       0
     170    0.06       0     250    0.05       0     640     0.1       0
   837.8   0.045       0   851.5     0.1       0     900    0.05       0
Bank Sta=837.8,851.5
XS Rating Curve= 0 ,0
Exp/Cntr(USF)=0,0
Exp/Cntr=0.3,0.1

Type RM Length L Ch R = 1 ,1275    ,77,77,77
BEGIN DESCRIPTION:
Structure XS 3
END DESCRIPTION:
XS GIS Cut Line= 6
2305871.48417076744436.9005313762305632.54790933 744451.59075704
2305591.70281854 744605.263856492305474.30328339744928.623537398
2305186.04318011745509.0108715832305196.24038453745989.830075472
#Sta/Elev= 30
       0 2037.26    67.4 2005.38    95.5 1994.27   135.6    1982   151.6 1970.26
   191.7 1971.93   207.7 1965.36   223.7 1963.03   261.7 1962.41   290.7 1959.22
   319.7 1958.41   653.6 1958.86   691.4 1960.36     805 1958.41   878.8 1959.91
   926.9 1956.18   958.9 1957.66   970.8 1955.64   976.7  1956.6   985.4 1955.23
   991.6 1956.81  1066.5 1959.06  1090.5 1956.92  1125.2 1957.37  1156.6 1960.65
  1215.2 1959.41  1389.2 1963.79  1694.6 1966.84  1748.4 1968.87  1871.6 1980.12
#Mann= 10, -1 ,  0
       0     0.1       0     120    0.08       0     220     0.1       0
   398.4    0.05       0   498.4     0.1       0   708.4    0.05       0
  822.41     0.1       0   976.7   0.045       0   991.6     0.1       0
 1010.96    0.05       0
Bank Sta=976.7,991.6
XS Rating Curve= 0 ,0
Exp/Cntr(USF)=0,0
Exp/Cntr=0.3,0.1

Type RM Length L Ch R = 1 ,1198    ,517.6,517.6,517.6
BEGIN DESCRIPTION:
Structure XS 2
END DESCRIPTION:
XS GIS Cut Line= 6
 2305842.2744193744372.3883028882305562.57478513744356.505998997
2305476.13331422744687.1379949312305362.44834141745008.640394668
2305113.19114271745477.5908586272305153.01822369745969.902785917
#Sta/Elev= 30
       0 2026.47    66.8 1994.59    90.2 1986.15   122.3 1977.56   138.3 1966.78
   142.3  1965.6   178.4 1968.65   194.4 1961.98   230.5 1961.86   242.5 1958.46
   274.5 1954.26   400.3 1953.97   446.2 1955.42   483.4 1954.02   645.8 1954.01
   841.9 1956.07   999.8 1959.29  1018.2 1956.68  1049.6 1957.32  1071.5 1955.82
  1092.2 1955.89  1099.4 1958.48  1138.2 1957.45  1283.1 1960.84  1461.5 1960.33
  1540.9 1965.33    1678  1963.9  1856.5 1966.93  1915.9 1969.86  1987.9 1977.36
#Mann= 11, -1 ,  0
       0     0.1       0      90    0.08       0     190    0.07       0
  330.15   0.025       0  430.15    0.07       0  540.15     0.1       0
   841.9    0.05       0   951.9     0.1       0 1062.91    0.05       0
  1071.5   0.045       0  1092.2    0.05       0
Bank Sta=1071.5,1092.2
XS Rating Curve= 0 ,0
Exp/Cntr(USF)=0,0
Exp/Cntr=0.3,0.1

Type RM Length L Ch R = 1 ,680     ,,,
BEGIN DESCRIPTION:
Structure XS 1
END DESCRIPTION:
XS GIS Cut Line= 4
2305823.60544205744311.0434484332305519.07159061744314.780060107
 2305065.0732722745547.8619125792305122.99075315746057.909406102
#Sta/Elev= 30
       0 2015.27    51.4 1992.21    71.4 1984.95   107.4 1974.42   119.4 1965.02
   123.4 1963.93   155.2 1966.47     207 1961.04   304.6 1958.03   328.4 1954.16
     516 1953.86   571.4 1954.23   605.5 1957.72   622.5 1955.17   648.61955.184
   956.7 1954.62   980.6 1957.59  1010.4 1957.77  1031.7 1956.36  1068.9 1958.54
  1158.1 1956.73  1189.5    1958  1497.8 1958.22  1619.9  1961.1  1691.2 1965.43
  1776.9 1963.97  1909.7 1966.18  1974.1 1968.27  2006.4 1970.63  2131.9 1985.13
#Mann= 12, -1 ,  0
       0     0.1       0      70    0.08       0     170    0.07       0
  404.56   0.025       0  474.56     0.1       0   622.5   0.045       0
   648.6     0.1       0 1044.56    0.05       0 1334.56     0.1       0
 1344.56    0.05       0 1614.56     0.1       0 1648.56    0.05       0
Bank Sta=622.5,648.6
XS Rating Curve= 0 ,0
Exp/Cntr(USF)=0,0
Exp/Cntr=0.3,0.1
LCMann Table=0

Chan Stop Cuts=-1
Use User Specified Reach Order=0
Composite Channel Slope=5